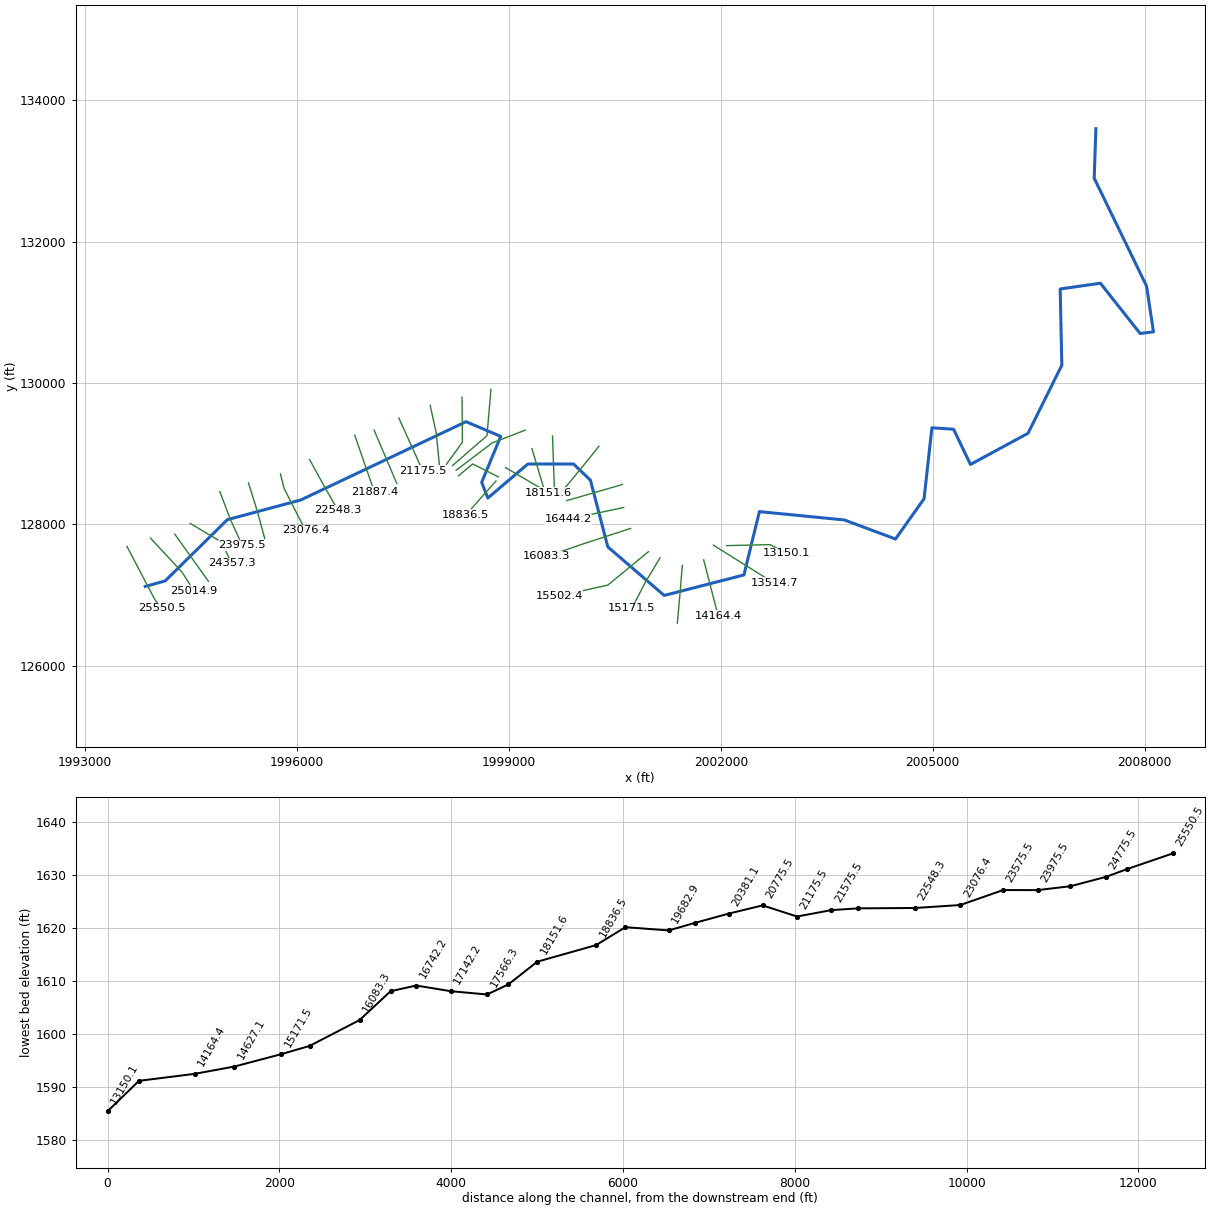
--- EastRiver2.prj (project) ---

Proj Title=EastRiver2
Current Plan=p01
Default Exp/Contr=0,0
English Units
Geom File=g01
Flow File=f01
Plan File=p01
BEGIN DESCRIPTION:
END DESCRIPTION:
DSS Export Rating Curves= 0
DSS Export Rating Curve Sorted= 0
DSS Export Volume Flow Curves= 0
DXF OffsetX= 0
DXF OffsetY= 0
DXF ScaleX= 0
DXF ScaleY= 0

--- EastRiver2.p01 (plan) ---

Plan Title=Floodplain
Program Version=4.00
Geom File=g01
Flow File=f01
K Sum by GR=0
Std Step Tol=0.01
Critical Tol=0.01
Num of Std Step Trials=20
Max Error Tol=0.3
Flow Tol Ratio=0.001
Split Flow NTrial=30
Split Flow Tol=0.02
Split Flow Ratio=0.02
Log Output Level=0
Friction Slope Method=1
Unsteady Friction Slope Method=2
Unsteady Bridges Friction Slope Method=1
Global Log Level=0
CheckData=False
Run HTab=0
Run UNet=0
Run PostProcess=0
UNET Theta=0
UNET Theta Warmup=0
UNET ZTol=0
UNET ZSATol=0
UNET MxIter=0
UNET MaxInSteps=0
UNET DtIC=0
UNET DtMin=0
UNET MaxCRTS=0
UNET WFStab=0
UNET SFStab=0
UNET WFX=0
UNET SFX=0
UNET DSS MLevel=0
UNET DZMax Abort=0
UNET Convert EG Bridges=0
UNET Use Existing IB Tables=0
UNET Froude Limit=0
UNET Froude Power=0
Write IC File=0
Echo Input=False
Echo Output=False
Write Detailed=0

--- EastRiver2.f01 (steady flow) ---

Flow Title=NFF Regression Equation
Program Version=4.10
Number of Profiles= 1
Profile Names=P100yr
River Rch & RM=EastRiver2,Main            ,25550.5
    8395
River Rch & RM=EastRiver2,Main            ,15502.4
 9180.01
River Rch & RM=EastRiver2,Main            ,342.2
9491.085
Boundary for River Rch & Prof#=EastRiver2,Main            , 1
Up Type= 0
Dn Type= 3
Dn Slope=0.003717
DSS Import GetInterval= 0
DSS Import GetPeak= 0
DSS Import FillOption= 0

--- EastRiver2.g01 (geometry) ---

Geom Title=USGS 3m DEM
Program Version=4.10

River Reach=EastRiver2      ,Main
Reach XY= 30
     1993849.933      127122.656     1994131.551      127200.265
     1995010.964      128066.201     1996052.108      128345.861
     1998391.269      129452.927     1998882.404      129245.491
     1998612.852      128595.197     1998700.457      128372.816
     1999266.516      128854.641      1999913.44      128854.641
     2000152.668      128625.522     2000398.634      127682.089
     2001197.182      126994.732     2002325.931        127284.5
     2002544.942      128180.761     2003747.817      128062.832
     2004472.238       127793.28     2004876.566      128362.708
     2004987.756      129366.789     2005294.372      129346.573
     2005533.599      128847.902     2006348.994      129289.293
     2006827.448      130252.942     2006803.863      131331.149
     2007373.291      131412.015     2007935.981      130701.072
     2008124.667      130724.657     2008026.955      131371.582
     2007285.687       132897.92     2007309.273      133598.755

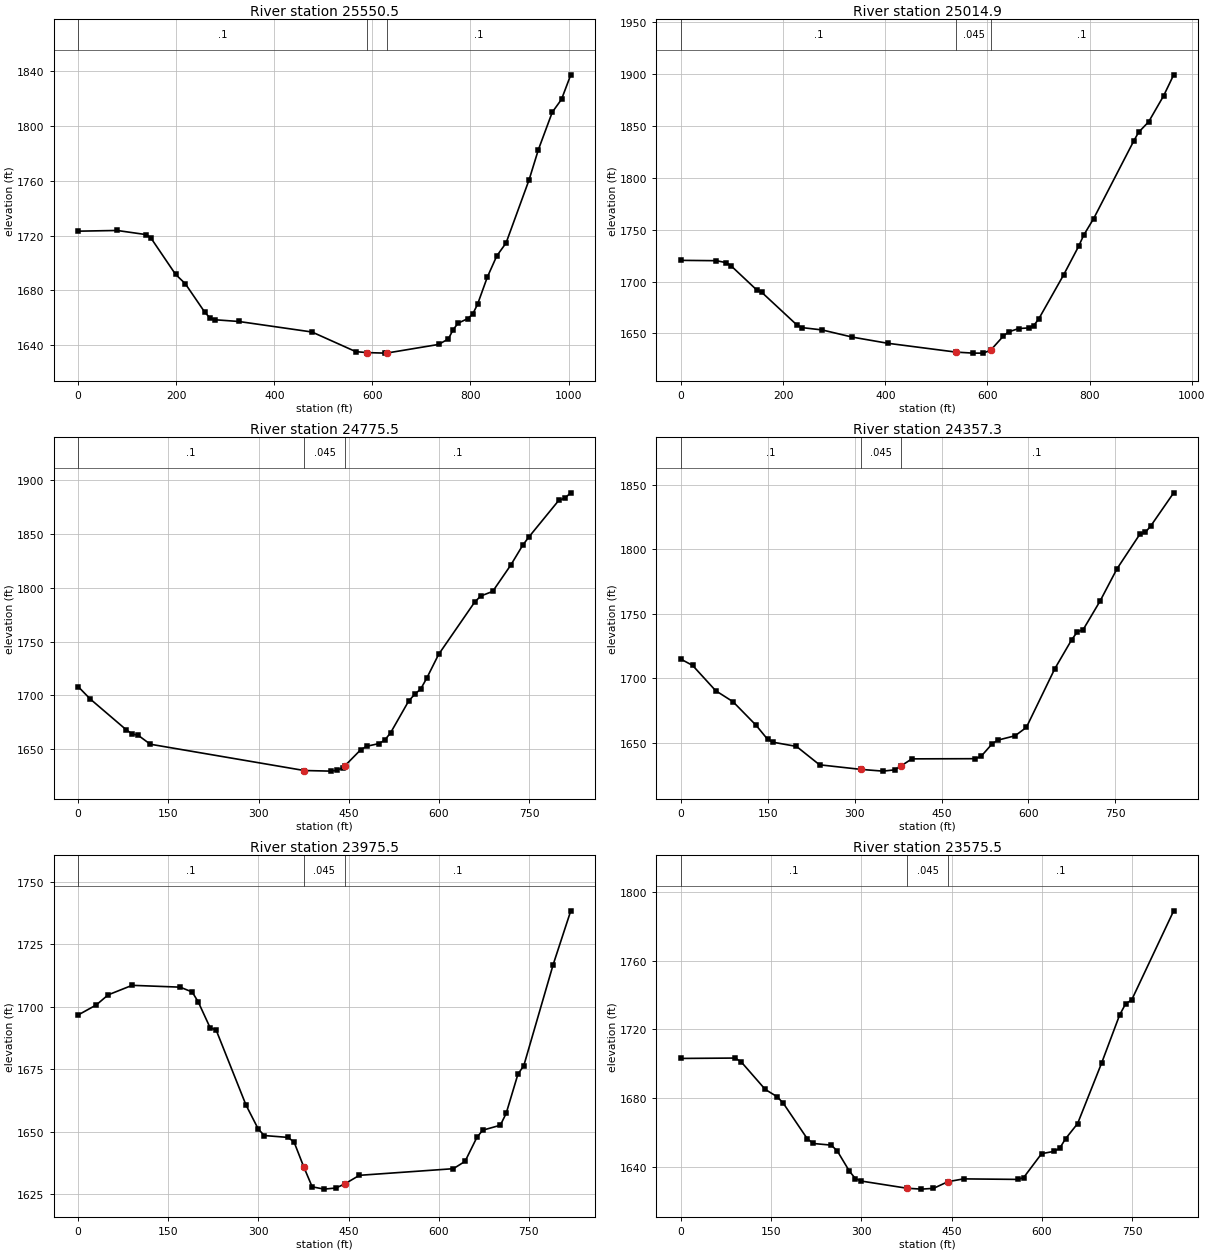
Type RM Length L Ch R = 1 ,25550.5 ,530.7,535.5,540.4
XS GIS Cut Line= 3
     1993590.971      127687.081     1993983.666      126939.642
     1994079.052      126810.851
#Sta/Elev= 30
       0 1723.19    79.5  1723.7   139.1 1720.65     149 1717.86   198.7 1691.57
   218.5 1684.75   258.3 1663.87   268.2 1659.94   278.1 1658.44   327.8 1657.14
   476.8 1649.46   566.2 1635.09   589.31634.401   625.8 1634.01   629.31634.052
     735 1640.36   754.9 1644.36   764.8  1651.2   774.8  1655.9   794.6 1659.26
   804.6 1662.53   814.5 1669.72   834.4 1689.56   853.8 1705.15   872.6 1714.52
   919.7 1760.86   938.6 1782.85   966.9  1810.2   985.7 1819.56  1004.6 1837.51
#Mann= 3 , 0 , 0
       0      .1       0   589.3    .045       0   629.3      .1       0
Bank Sta=589.3,629.3
XS Rating Curve= 0 ,0
Exp/Cntr=0.3,0.1

Type RM Length L Ch R = 1 ,25014.9 ,242.2,239.5,236.7
XS GIS Cut Line= 3
     1993924.312       127804.93     1994367.771      127328.139
     1994536.691        127063.8
#Sta/Elev= 30
       0  1720.4    69.1 1720.07    88.8 1718.13    98.7 1714.75     148 1691.97
   157.8  1689.7   226.9 1658.12   236.8 1655.62   276.2 1653.38   335.4 1646.46
   404.5 1640.55   538.61632.017   572.2 1631.04     592 1631.04   606.61634.019
   631.4 1647.54   641.3 1651.46     661 1654.68   680.6 1655.33   690.4 1657.44
   700.2 1663.72   749.2 1706.37   778.6  1733.9   788.4 1744.52     808  1760.6
   886.4 1835.21   896.2 1843.85   915.8 1853.87   945.2    1879   964.8  1899.1
#Mann= 3 , 0 , 0
       0      .1       0   538.6    .045       0   606.6      .1       0
Bank Sta=538.6,606.6
XS Rating Curve= 0 ,0
Exp/Cntr=0.3,0.1

Type RM Length L Ch R = 1 ,24775.5 ,409.5,418.2,426.9
XS GIS Cut Line= 3
     1994268.581      127860.597     1994506.851      127527.274
     1994744.537      127193.957
#Sta/Elev= 30
       0  1708.1      20 1696.62      80 1667.98    89.9 1664.09    99.9 1662.85
   119.9 1654.59   375.71630.177   419.7  1629.6   429.7 1630.26   439.7 1632.68
   443.71634.652   469.6 1649.33   479.6 1652.68   499.6 1655.12   509.6 1658.26
   519.6 1665.31   549.5 1694.67   559.5 1700.94   569.5 1705.82   579.5 1715.84
   599.4 1738.07   659.4 1786.67   669.3 1792.25   689.3 1796.58   719.3 1820.97
   739.2 1839.45   749.2 1846.95   799.1 1881.08   809.1 1883.19   819.1 1888.14
#Mann= 3 , 0 , 0
       0      .1       0   375.7    .045       0   443.7      .1       0
Bank Sta=375.7,443.7
XS Rating Curve= 0 ,0
Exp/Cntr=0.3,0.1

Type RM Length L Ch R = 1 ,24357.3 ,396.2,381.8,368.8
XS GIS Cut Line= 3
     1994486.366      128013.773     1994931.756      127748.653
     1995072.813      127447.216
#Sta/Elev= 30
       0 1714.68    19.9 1709.92    59.8 1690.27    89.7 1681.73   129.6 1663.42
   149.5  1652.5   159.5 1650.22   199.4    1647   239.2 1632.73   311.5 1629.13
   348.9 1627.82   368.8  1628.8   379.51631.697   398.7 1637.34   508.4 1637.48
   518.3 1639.26   537.9 1649.25   547.7 1651.94   577.1 1655.28   596.6 1661.79
   645.6 1707.26   674.9 1729.88   684.7 1736.02   694.5 1737.56   723.9 1759.88
   753.2 1784.98   792.4 1811.63   802.2 1813.26     812 1818.55   851.1 1843.94
#Mann= 3 , 0 , 0
       0      .1       0   311.5    .045       0   379.5      .1       0
Bank Sta=311.5,379.5
XS Rating Curve= 0 ,0
Exp/Cntr=0.3,0.1

Type RM Length L Ch R = 1 ,23975.5 ,401.2,400,396.6
XS GIS Cut Line= 3
     1994905.957      128464.084      1995050.61      128081.179
     1995220.121      127707.274
#Sta/Elev= 30
       0 1696.73      30 1700.72    49.9 1704.77    89.8 1708.58   169.7 1707.85
   189.7 1705.92   199.7 1702.01   219.6 1691.62   229.6 1690.72   279.5 1660.61
   299.5 1651.22   309.5 1648.52   349.4 1647.77   359.4 1645.86   375.31636.063
   389.4 1628.02   409.3 1627.09   428.9 1627.54   443.31629.123     468 1632.61
   624.4 1635.26   643.9  1638.2   663.5 1647.75   673.2 1650.65   702.6 1652.64
   712.3 1657.39   731.9 1673.08   741.6 1676.44   790.5 1716.86   819.8 1738.37
#Mann= 3 , 0 , 0
       0      .1       0   375.3    .045       0   443.3      .1       0
Bank Sta=375.3,443.3
XS Rating Curve= 0 ,0
Exp/Cntr=0.3,0.1

Type RM Length L Ch R = 1 ,23575.5 ,494.4,499,504.5
XS GIS Cut Line= 3
     1995311.181      128586.381     1995433.539      128195.233
      1995541.27       127800.22
#Sta/Elev= 30
       0 1703.14      90 1703.36     100 1701.12     140  1685.1   159.9 1680.83
   169.9 1677.11   209.9 1656.41   219.9 1653.65   249.9 1652.69   259.9 1649.23
   279.9 1637.57   289.9 1633.23   299.9 1631.78   375.81627.612   399.8  1627.1
   419.8 1627.55   443.81631.424   469.8 1633.06   559.6 1632.76   569.6 1633.75
   599.6 1647.73   619.6 1649.03   629.5 1650.76   639.5 1656.44   659.5 1665.23
   699.4 1700.42   729.4 1728.43   739.4 1734.96   749.4 1737.15   819.3 1789.02
#Mann= 3 , 0 , 0
       0      .1       0   375.8    .045       0   443.8      .1       0
Bank Sta=375.8,443.8
XS Rating Curve= 0 ,0
Exp/Cntr=0.3,0.1

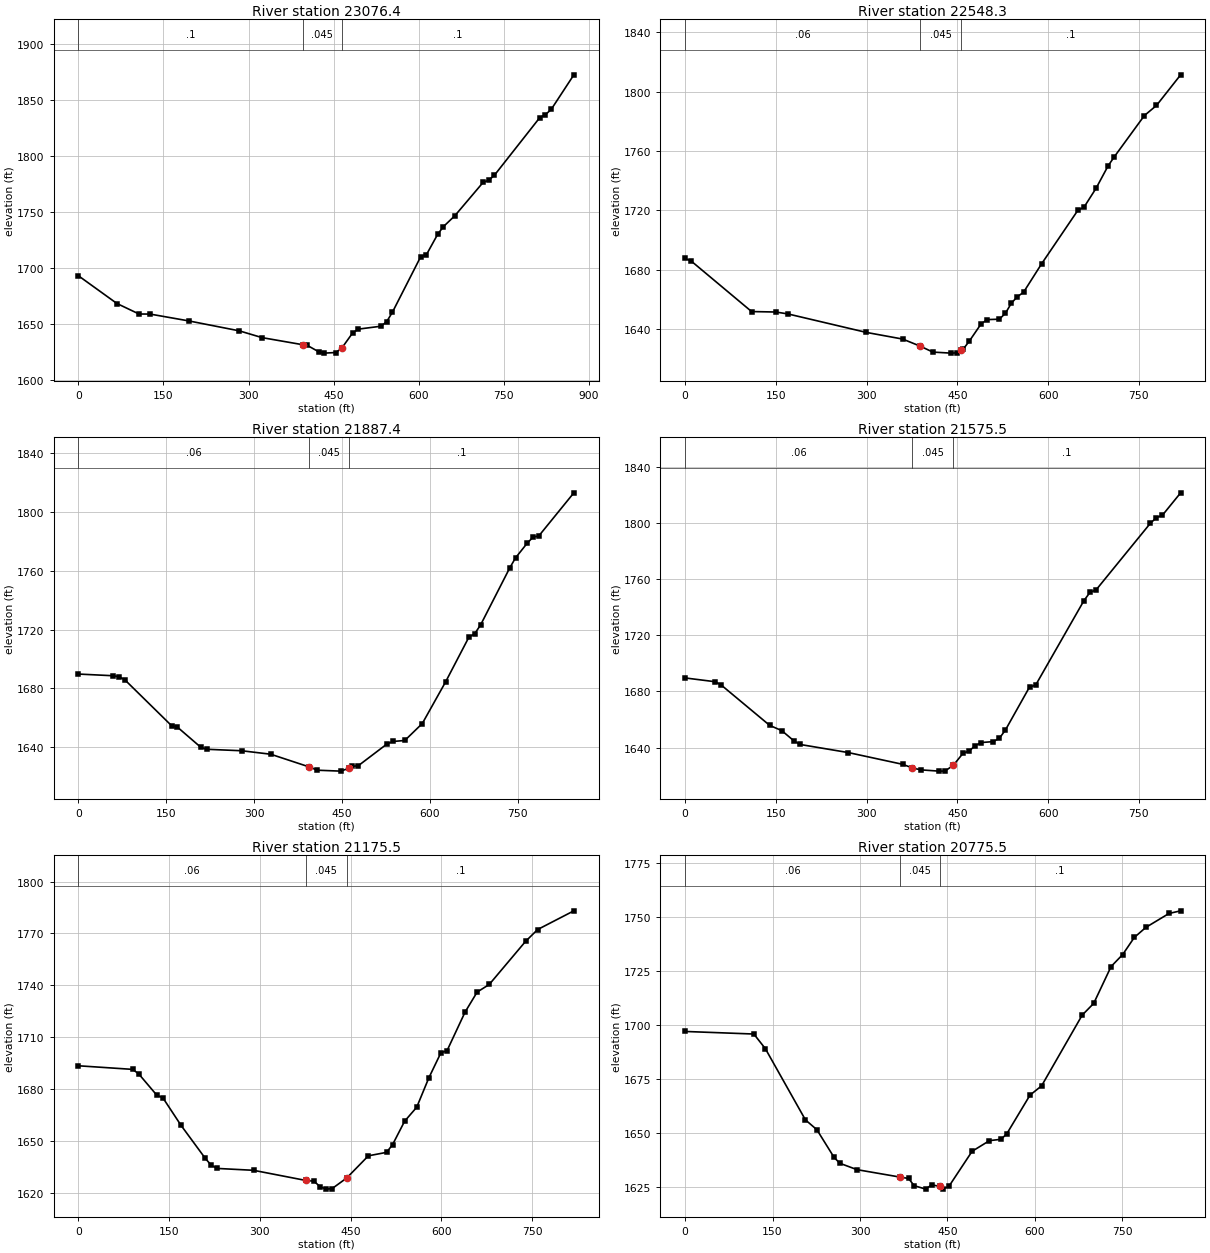
Type RM Length L Ch R = 1 ,23076.4 ,528.4,528.2,528.1
XS GIS Cut Line= 3
     1995763.485      128713.271     1995816.742      128506.108
     1996116.246      127918.694
#Sta/Elev= 30
       0 1693.27    68.1 1668.48     107 1659.13   126.4 1659.08   194.4 1653.01
   283.8 1644.12   323.8 1638.09     3961631.738   403.7 1631.13   423.7 1625.47
   433.7 1624.28   453.7 1624.83     4641628.535   483.6 1642.37   493.6 1645.67
   533.6 1648.27   543.6 1652.45   553.6 1660.78   603.5 1710.28   613.5    1712
   633.5 1730.33   643.5 1737.02   663.5 1746.65   713.4 1776.41   723.4 1778.35
   733.4 1782.83   813.3 1834.15   823.3 1836.83   833.3 1841.36   873.3 1872.24
#Mann= 3 , 0 , 0
       0      .1       0     396    .045       0     464      .1       0
Bank Sta=396,464
XS Rating Curve= 0 ,0
Exp/Cntr=0.3,0.1

Type RM Length L Ch R = 1 ,22548.3 ,664.6,660.9,657
XS GIS Cut Line= 3
     1996176.811      128915.757     1996374.628      128557.213
     1996576.355      128200.813
#Sta/Elev= 30
       0 1687.54      10 1685.82   109.9 1651.74   149.8 1651.44   169.8 1650.16
   299.6 1637.68   359.6  1633.2   388.41628.443   409.5 1624.42   439.5 1623.72
   449.4  1623.9   456.41625.587   459.4 1626.31   469.4 1631.62   489.4 1643.54
   499.4 1646.32   519.4  1646.6   529.4 1650.58   539.4  1657.5   549.3  1661.8
   559.3 1664.73   589.3    1684   649.2 1720.04   659.2 1722.04   679.2 1734.84
   699.2 1750.02   709.2 1755.99   759.1 1783.89   779.1 1790.69     819 1811.34
#Mann= 3 , 0 , 0
       0     .06       0   388.4    .045       0   456.4      .1       0
Bank Sta=388.4,456.4
XS Rating Curve= 0 ,0
Exp/Cntr=0.3,0.1

Type RM Length L Ch R = 1 ,21887.4 ,310.5,311.9,313.4
XS GIS Cut Line= 2
     1996815.733      129261.631     1997093.036      128462.156
#Sta/Elev= 30
       0 1689.76    59.7  1688.6    69.7 1687.93    79.6 1685.77   159.3 1654.57
   169.2 1653.63   209.1 1639.91     219 1638.54   278.8 1637.53   328.5 1635.17
   394.31626.514   408.2 1624.27     448 1623.65   462.31625.591   467.9 1626.98
   477.9 1627.27   527.6  1642.3   537.6 1643.85   557.5 1644.53   587.4 1656.07
   627.2 1684.43     667 1714.89     677 1717.31   686.9 1723.17   736.7 1762.03
   746.6 1768.87   766.6 1778.91   776.5 1782.97   786.5 1783.88   846.2 1813.17
#Mann= 3 , 0 , 0
       0     .06       0   394.3    .045       0   462.3      .1       0
Bank Sta=394.3,462.3
XS Rating Curve= 0 ,0
Exp/Cntr=0.3,0.1

Type RM Length L Ch R = 1 ,21575.5 ,399.5,400,400.5
XS GIS Cut Line= 3
     1997089.916      129333.803     1997250.088      128956.927
      1997410.26      128580.052
#Sta/Elev= 30
       0 1689.61    49.9  1686.9    59.9 1684.49   139.8 1655.86   159.8 1652.12
   179.8 1644.87   189.8  1642.3   269.7 1636.52   359.6 1628.16   375.51625.616
   389.5 1624.22   419.5 1623.32   429.5 1623.34   443.51627.564   459.4 1636.04
   469.4 1637.61   479.4 1641.41   489.4 1643.66   509.4 1644.32   519.4 1646.68
   529.4 1652.56   569.3 1683.17   579.3 1684.46   659.2 1744.62   669.2 1750.49
   679.2 1752.21   769.1 1799.69     779 1803.62     789  1805.4     819 1821.28
#Mann= 3 , 0 , 0
       0     .06       0   375.5    .045       0   443.5      .1       0
Bank Sta=375.5,443.5
XS Rating Curve= 0 ,0
Exp/Cntr=0.3,0.1

Type RM Length L Ch R = 1 ,21175.5 ,404.5,400,393.1
XS GIS Cut Line= 3
     1997440.376      129504.847     1997609.159      129131.749
     1997777.942       128758.65
#Sta/Elev= 30
       0 1693.47    89.9 1691.38    99.9 1688.74   129.8 1676.42   139.8 1674.92
   169.8 1658.98   209.7 1639.98   219.7  1635.9   229.7 1634.08   289.6    1633
   375.51627.162   389.5 1626.71   399.5 1623.55   409.5 1622.11   419.5 1622.43
   443.51628.523   479.4 1641.38   509.4 1643.38   519.4 1647.86   539.3  1661.4
   559.3 1669.49   579.3 1686.46   599.3 1701.03   609.3 1702.13   639.2 1724.53
   659.2 1736.12   679.2 1740.52   739.1  1765.4   759.1 1772.28     819 1783.11
#Mann= 3 , 0 , 0
       0     .06       0   375.5    .045       0   443.5      .1       0
Bank Sta=375.5,443.5
XS Rating Curve= 0 ,0
Exp/Cntr=0.3,0.1

Type RM Length L Ch R = 1 ,20775.5 ,399.3,394.4,392
XS GIS Cut Line= 3
     1997884.013      129684.201     1997969.594       129290.53
     1998014.046      128845.655
#Sta/Elev= 30
       0 1697.13   117.9 1695.94   137.6  1689.2   206.4 1656.24     226  1651.7
   255.5 1638.91   265.3 1636.18   294.8 1633.22   368.91629.768   383.2 1629.15
     393  1625.8   412.8 1624.21   422.7 1626.19   436.91625.503   442.6  1624.3
   452.5 1625.48   492.3 1641.71   522.1 1646.64     542 1647.26   551.9 1649.85
   591.6 1667.68   611.5 1671.98   681.1 1704.68   700.9 1710.12   730.7 1727.16
   750.6 1732.71   770.5  1740.6   790.3 1745.25   830.1 1751.71     850 1752.92
#Mann= 3 , 0 , 0
       0     .06       0   368.9    .045       0   436.9      .1       0
Bank Sta=368.9,436.9
XS Rating Curve= 0 ,0
Exp/Cntr=0.3,0.1

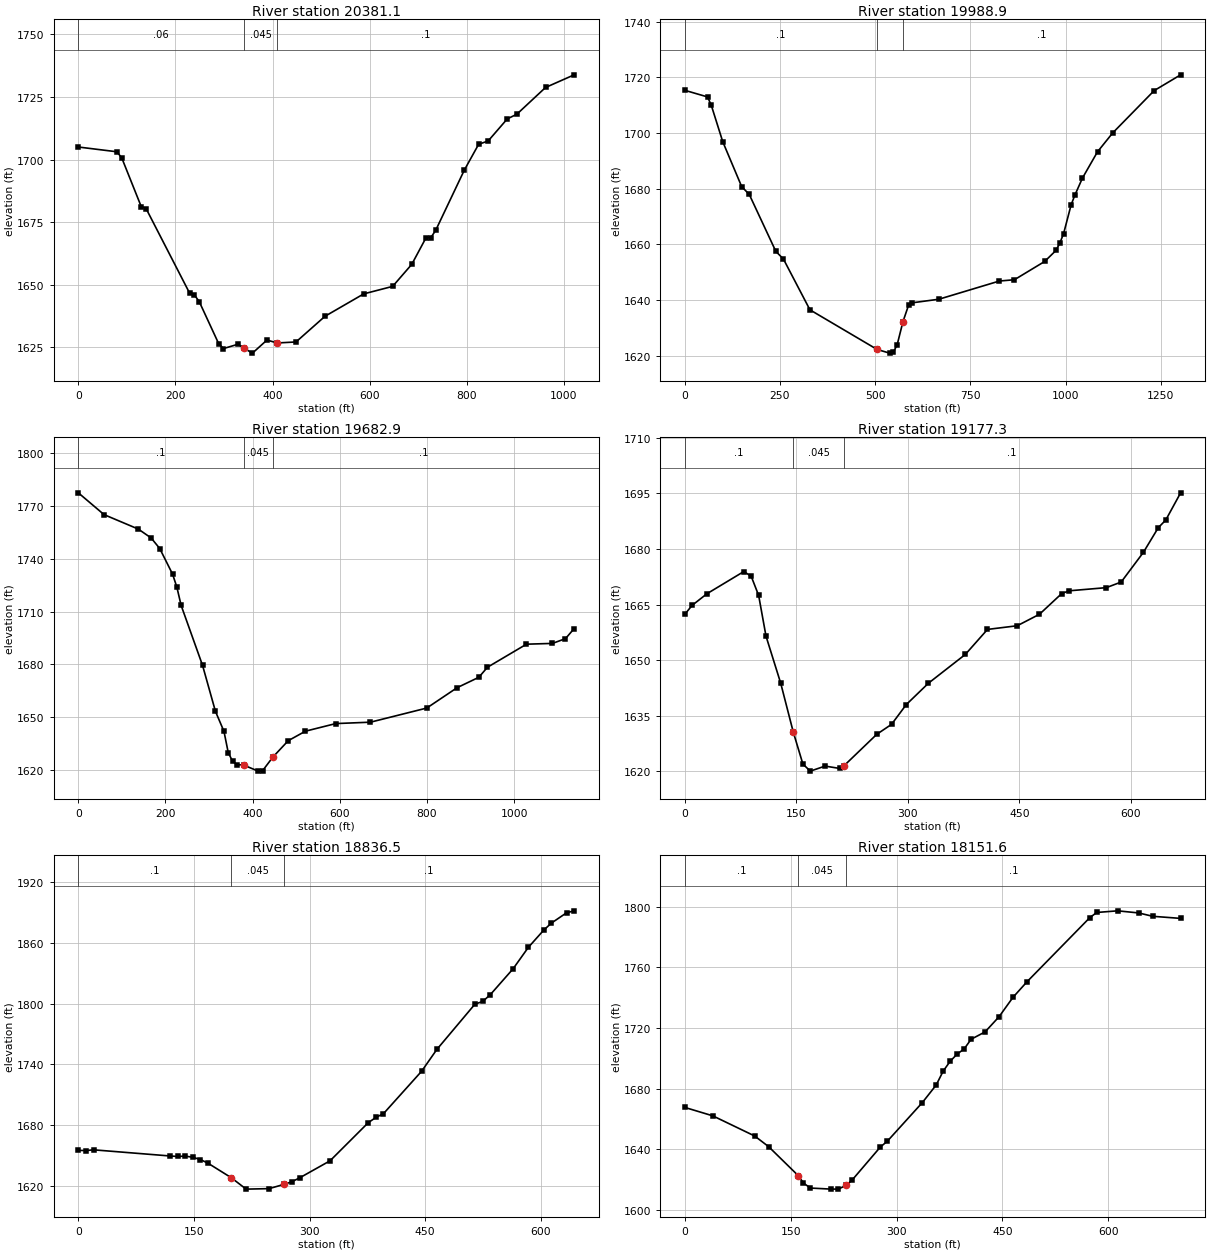
Type RM Length L Ch R = 1 ,20381.1 ,393.8,392.1,390.4
XS GIS Cut Line= 3
     1998334.508      129800.738     1998340.305      129163.084
     1998114.923      128852.549
#Sta/Elev= 30
       0 1705.01    79.7  1703.1    89.7 1700.55   129.5 1681.23   139.5 1680.44
   229.2 1646.64   239.1 1645.91   249.1 1643.22     289 1626.49   298.9 1624.48
   328.8  1626.2   341.5 1624.57   358.7 1622.66   388.6 1627.89   409.5 1626.72
   448.4 1627.12   508.2 1637.39   587.9 1646.33   647.5 1649.33   686.9 1658.14
   716.4 1668.82   726.2 1668.84   736.1 1671.69   795.1 1695.77   824.6 1706.09
   844.3 1707.44   883.6 1716.24   903.3 1718.11   962.4 1728.79  1021.4 1733.85
#Mann= 3 , 0 , 0
       0     .06       0   341.5    .045       0   409.5      .1       0
Bank Sta=341.5,409.5
XS Rating Curve= 0 ,0
Exp/Cntr=0.3,0.1

Type RM Length L Ch R = 1 ,19988.9 ,329.9,306.4,282.9
XS GIS Cut Line= 3
     1998744.152      129910.878     1998688.116      129255.834
     1998201.186      128833.048
#Sta/Elev= 30
       0 1715.31    59.8 1712.93    69.7 1709.88    99.6 1696.88   149.4 1680.72
   169.3 1677.92   239.1 1657.47     259 1654.72   328.7 1636.47   505.11622.243
   537.9 1620.92   547.9  1621.3   557.8 1623.94   573.11632.264   587.7 1638.12
   597.7    1639   667.4 1640.28   826.1 1646.81   865.8 1647.28   945.2 1653.84
   974.9  1657.8   984.8 1660.38   994.8 1663.78  1014.6 1674.14  1024.5 1677.65
  1044.4 1683.78    1084 1693.23  1123.7 1699.97  1232.8  1715.2  1302.3 1720.87
#Mann= 3 , 0 , 0
       0      .1       0   505.1    .045       0   573.1      .1       0
Bank Sta=505.1,573.1
XS Rating Curve= 0 ,0
Exp/Cntr=0.3,0.1

Type RM Length L Ch R = 1 ,19682.9 ,523.4,505.2,487
XS GIS Cut Line= 3
     1999227.062      129332.638     1998759.611      129151.491
      1998252.38      128767.099
#Sta/Elev= 30
       0 1777.34      59 1764.98   137.6 1756.78   167.1 1751.73   186.8 1745.75
   216.3  1731.2   226.1 1723.84   235.9 1713.49   285.1 1679.42   314.6 1653.42
   334.2 1642.03     344 1629.99   353.9 1625.12   363.6 1623.18   379.21622.927
   412.8 1619.49   422.7  1619.7   446.51627.479   481.7 1636.76   521.2 1642.15
   590.8 1646.46   670.4 1647.25   799.6 1655.27   869.3 1666.83     919 1672.71
   938.9 1678.42  1028.4 1691.49    1088 1691.93  1117.9 1694.64  1137.8 1700.35
#Mann= 3 , 0 , 0
       0      .1       0   379.2    .045       0   446.5      .1       0
Bank Sta=379.2,446.5
XS Rating Curve= 0 ,0
Exp/Cntr=0.3,0.1

Type RM Length L Ch R = 1 ,19177.3 ,312.6,340.8,369
XS GIS Cut Line= 3
     1998848.496      128672.284     1998485.226      128855.851
     1998286.914      128688.258
#Sta/Elev= 30
       0 1662.41     9.9 1664.83    29.8 1667.96    79.4 1673.95    89.3 1672.66
    99.3  1667.5   109.2 1656.51     129 1643.79   145.81630.679   158.8    1622
   168.8  1620.1   188.6 1621.46   208.5 1620.82   213.81621.495   258.1 1630.03
     278 1632.72   297.8 1638.05   327.6 1643.82   377.2 1651.58     407 1658.33
     447 1659.32   476.9 1662.42   506.9 1668.02   516.9 1668.75   566.8  1669.6
   586.8 1671.12   616.7 1679.14   636.7 1685.79   646.7 1687.83   666.7 1695.18
#Mann= 3 , 0 , 0
       0      .1       0   145.8    .045       0   213.8      .1       0
Bank Sta=145.8,213.8
XS Rating Curve= 0 ,0
Exp/Cntr=0.3,0.1

Type RM Length L Ch R = 1 ,18836.5 ,647.3,684.9,722.5
XS GIS Cut Line= 2
     1998815.647      128614.316     1998388.612      128133.177
#Sta/Elev= 30
       0 1655.04     9.9 1654.85    19.8 1655.58   118.8 1649.51   128.7 1649.02
   138.6 1649.38   148.5 1648.24   158.4 1645.96   168.2 1642.37   198.61627.914
   217.7 1616.72   247.4 1617.21   266.61621.354   277.1 1624.02     287 1627.81
   326.6 1644.74   376.1 1682.38     386  1687.6   395.9 1691.32   445.4 1733.29
   465.2 1754.88   514.6 1799.63   524.6 1802.25   534.4 1808.89   564.1 1834.59
   583.9  1855.8   603.7 1872.68   613.6 1879.66   633.4 1889.92   643.3 1891.88
#Mann= 3 , 0 , 0
       0      .1       0   198.6    .045       0   266.6      .1       0
Bank Sta=198.6,266.6
XS Rating Curve= 0 ,0
Exp/Cntr=0.3,0.1

Type RM Length L Ch R = 1 ,18151.6 ,352.6,336.6,320.7
XS GIS Cut Line= 2
     1998950.907       128803.68     1999557.402      128448.985
#Sta/Elev= 30
       0 1667.56    39.6 1662.01      99 1648.69   118.8 1641.64     1611622.389
   168.2 1617.56   178.1  1614.3   207.8 1613.59   217.7 1613.65     2291616.168
   237.5  1619.8   277.1  1641.4     287 1645.24   336.5  1670.7   356.2 1682.33
   366.1 1691.51     376 1698.01   385.9  1702.8   395.8 1706.15   405.7 1712.58
   425.5 1717.44   445.3 1727.46   465.1  1740.3   484.9 1750.55     574 1792.95
   583.8 1796.33   613.5 1797.41   643.2 1796.01     663  1793.8   702.6 1792.41
#Mann= 3 , 0 , 0
       0      .1       0     161    .045       0     229      .1       0
Bank Sta=161,229
XS Rating Curve= 0 ,0
Exp/Cntr=0.3,0.1

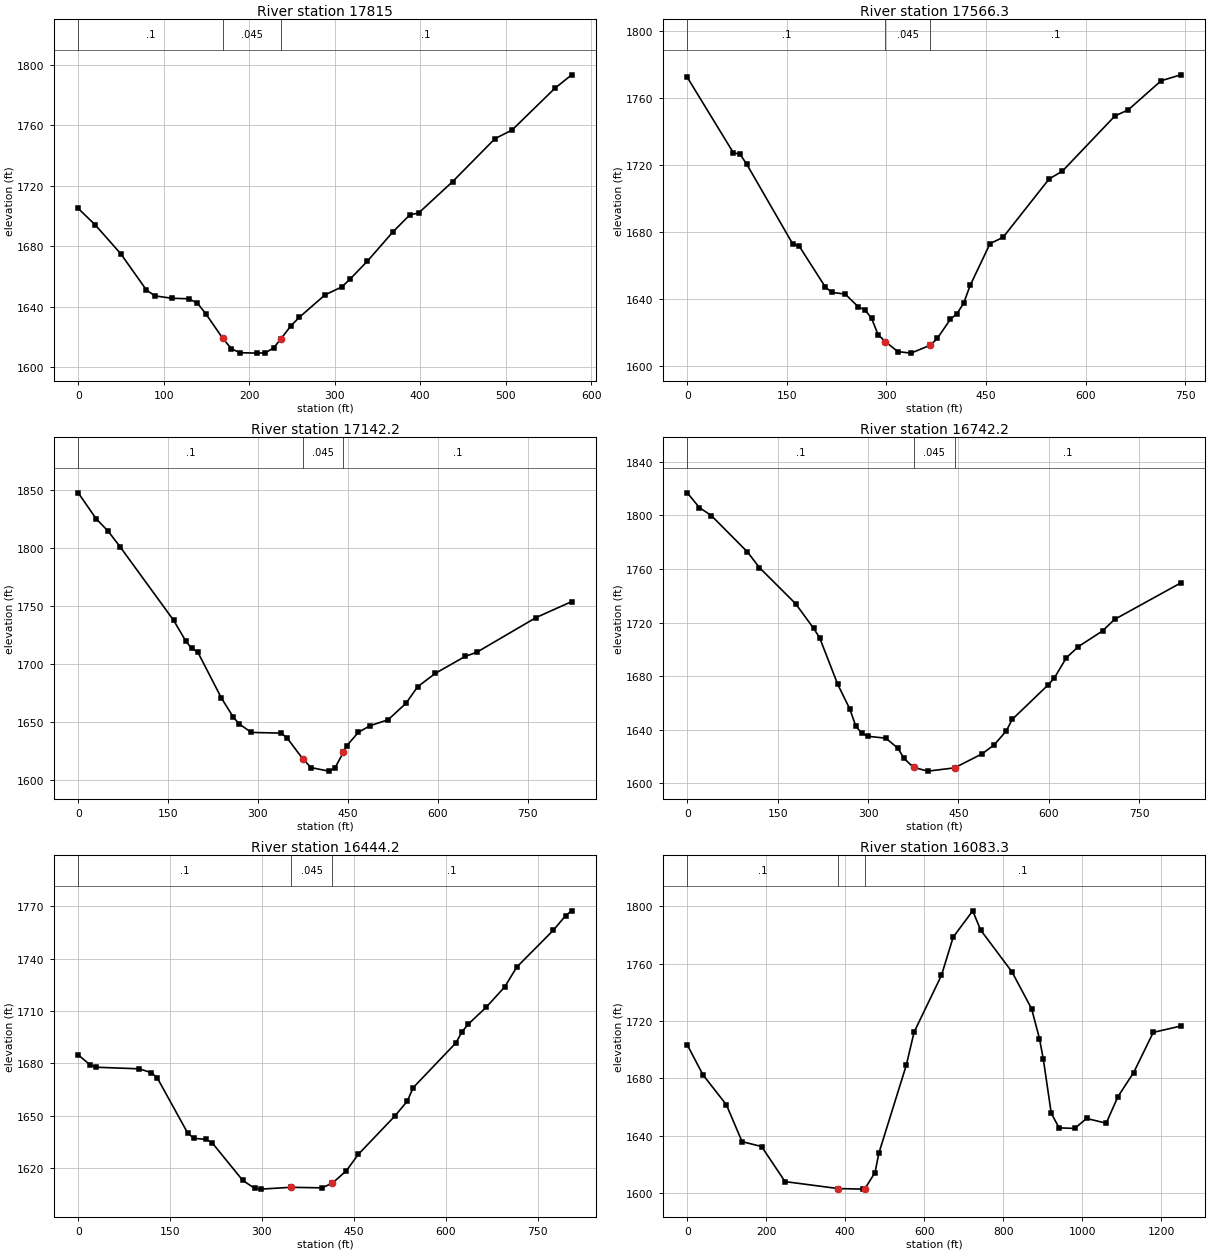
Type RM Length L Ch R = 1 ,17815   ,254,248.6,243.3
XS GIS Cut Line= 2
     1999324.646      129071.521     1999490.014      128518.668
#Sta/Elev= 30
       0 1704.98    19.9  1694.1    49.8 1674.97    79.6  1651.2    89.5 1647.18
   109.4 1645.61   129.3 1645.24   139.3  1642.4   149.2 1635.35   168.91619.203
   179.1 1612.24     189 1609.61   208.9 1609.31   218.9  1609.5   228.8 1612.91
   236.91618.629   248.7 1627.34   258.7 1633.06   288.5 1647.75   308.4 1653.12
   318.4 1658.54   338.3 1670.17   368.1 1689.51     388 1700.83     398  1701.9
   437.8 1722.68   487.5 1751.16   507.4 1756.82   557.2 1784.29   577.1 1793.33
#Mann= 3 , 0 , 0
       0      .1       0   168.9    .045       0   236.9      .1       0
Bank Sta=168.9,236.9
XS Rating Curve= 0 ,0
Exp/Cntr=0.3,0.1

Type RM Length L Ch R = 1 ,17566.3 ,439.3,424.1,408.8
XS GIS Cut Line= 2
     1999615.612      129250.037     1999642.508       128507.28
#Sta/Elev= 30
       0 1772.18    69.4 1727.11    79.3  1726.3    89.2  1720.5   158.6 1672.78
   168.5 1671.37   208.1 1646.77     218 1643.65   237.8 1642.71   257.7 1634.99
   267.6 1633.27   277.5 1628.24   287.4 1618.42   298.31614.284   317.1  1608.3
   336.9 1607.41   366.3  1612.2   376.6 1616.24   396.4 1627.71   406.3 1631.07
   416.2  1637.2   426.1 1647.92   455.9 1672.78   475.7 1676.66     545 1711.49
   564.9 1716.12   644.1 1749.13     664 1752.72   713.5 1770.11   743.2 1773.69
#Mann= 3 , 0 , 0
       0      .1       0   298.3    .045       0   366.3      .1       0
Bank Sta=298.3,366.3
XS Rating Curve= 0 ,0
Exp/Cntr=0.3,0.1

Type RM Length L Ch R = 1 ,17142.2 ,412.9,400,387.4
XS GIS Cut Line= 3
     2000272.865      129104.376     2000016.174      128786.567
     1999751.236      128467.114
#Sta/Elev= 30
       0 1847.82    29.9 1825.48    49.8  1814.9    69.8  1801.4   159.4 1737.85
   179.4 1720.25   189.3 1713.76   199.3 1710.84   239.1 1670.94   259.1 1654.34
     269 1648.58     289 1641.39   338.8 1640.78   348.7 1636.58   374.51618.835
   388.6 1611.06   418.4 1608.04   428.3 1610.59   442.51624.116     448 1629.74
   467.8 1641.59   487.6 1647.28   517.2 1652.27   546.9  1666.4   566.6 1680.79
   596.3 1692.34   645.7 1706.85   665.4  1710.5   764.3 1740.39   823.6 1754.09
#Mann= 3 , 0 , 0
       0      .1       0   374.5    .045       0   442.5      .1       0
Bank Sta=374.5,442.5
XS Rating Curve= 0 ,0
Exp/Cntr=0.3,0.1

Type RM Length L Ch R = 1 ,16742.2 ,299.5,298,296.6
XS GIS Cut Line= 3
     2000606.389      128564.528     2000213.038      128450.663
     1999819.687      128336.798
#Sta/Elev= 30
       0 1816.87      20 1805.88      40 1799.85    99.9 1772.71   119.8    1761
   179.8  1734.1   209.7  1715.7   219.7 1708.61   249.7 1673.86   269.7 1655.52
   279.7 1642.66   289.6 1637.38   299.6 1635.12   329.6 1633.69   349.6 1626.19
   359.6 1618.64   375.51611.877   399.5  1609.1   443.51611.535   489.4 1622.03
   509.4 1628.75   529.4 1639.07   539.3 1647.73   599.3 1673.64   609.3 1678.73
   629.2 1693.76   649.2 1702.09   689.2 1713.78   709.1 1722.35     819 1749.59
#Mann= 3 , 0 , 0
       0      .1       0   375.5    .045       0   443.5      .1       0
Bank Sta=375.5,443.5
XS Rating Curve= 0 ,0
Exp/Cntr=0.3,0.1

Type RM Length L Ch R = 1 ,16444.2 ,358.8,360.9,363.1
XS GIS Cut Line= 2
     2000624.265      128239.453     1999836.142      128071.963
#Sta/Elev= 30
       0 1684.89    19.9 1679.02    29.8  1677.8    99.5  1676.9   119.4 1674.71
   129.3 1671.56     179 1639.98     189 1637.14   208.9 1636.46   218.8 1634.51
   268.6 1613.03   288.5  1608.4   298.4 1608.03   346.91609.073   397.9 1608.76
   414.91611.427   437.7  1618.5   457.6 1628.04   517.2 1649.94   537.2 1658.34
   547.1 1666.18   616.7 1691.75   626.7 1698.12   636.6 1702.35   666.5 1712.28
   696.3 1723.77   716.2 1735.18   775.9 1756.25   795.8 1764.58   805.7 1767.34
#Mann= 3 , 0 , 0
       0      .1       0   346.9    .045       0   414.9      .1       0
Bank Sta=346.9,414.9
XS Rating Curve= 0 ,0
Exp/Cntr=0.3,0.1

Type RM Length L Ch R = 1 ,16083.3 ,572.8,580.8,588.8
XS GIS Cut Line= 3
     2000722.054      127943.371     2000025.257      127715.804
     1999536.389      127547.695
#Sta/Elev= 30
       0 1703.24    39.6 1682.39    99.1 1661.42   138.7 1635.72   188.2 1632.32
   247.6 1607.84   381.81602.996   445.8 1602.59   449.81602.857   475.5 1614.13
   485.4  1627.8   554.7 1689.02   574.5 1712.13   643.9 1751.82   673.6 1778.49
   723.1  1796.8     743 1783.44   822.5 1754.18   872.2 1728.47   892.1 1707.64
     902 1693.11   921.9 1655.62   941.8 1645.33   981.6 1644.96  1011.4 1651.92
  1061.1 1648.59  1090.9 1667.12  1130.7 1683.93  1180.4 1711.96    1250  1716.4
#Mann= 3 , 0 , 0
       0      .1       0   381.8    .045       0   449.8      .1       0
Bank Sta=381.8,449.8
XS Rating Curve= 0 ,0
Exp/Cntr=0.3,0.1

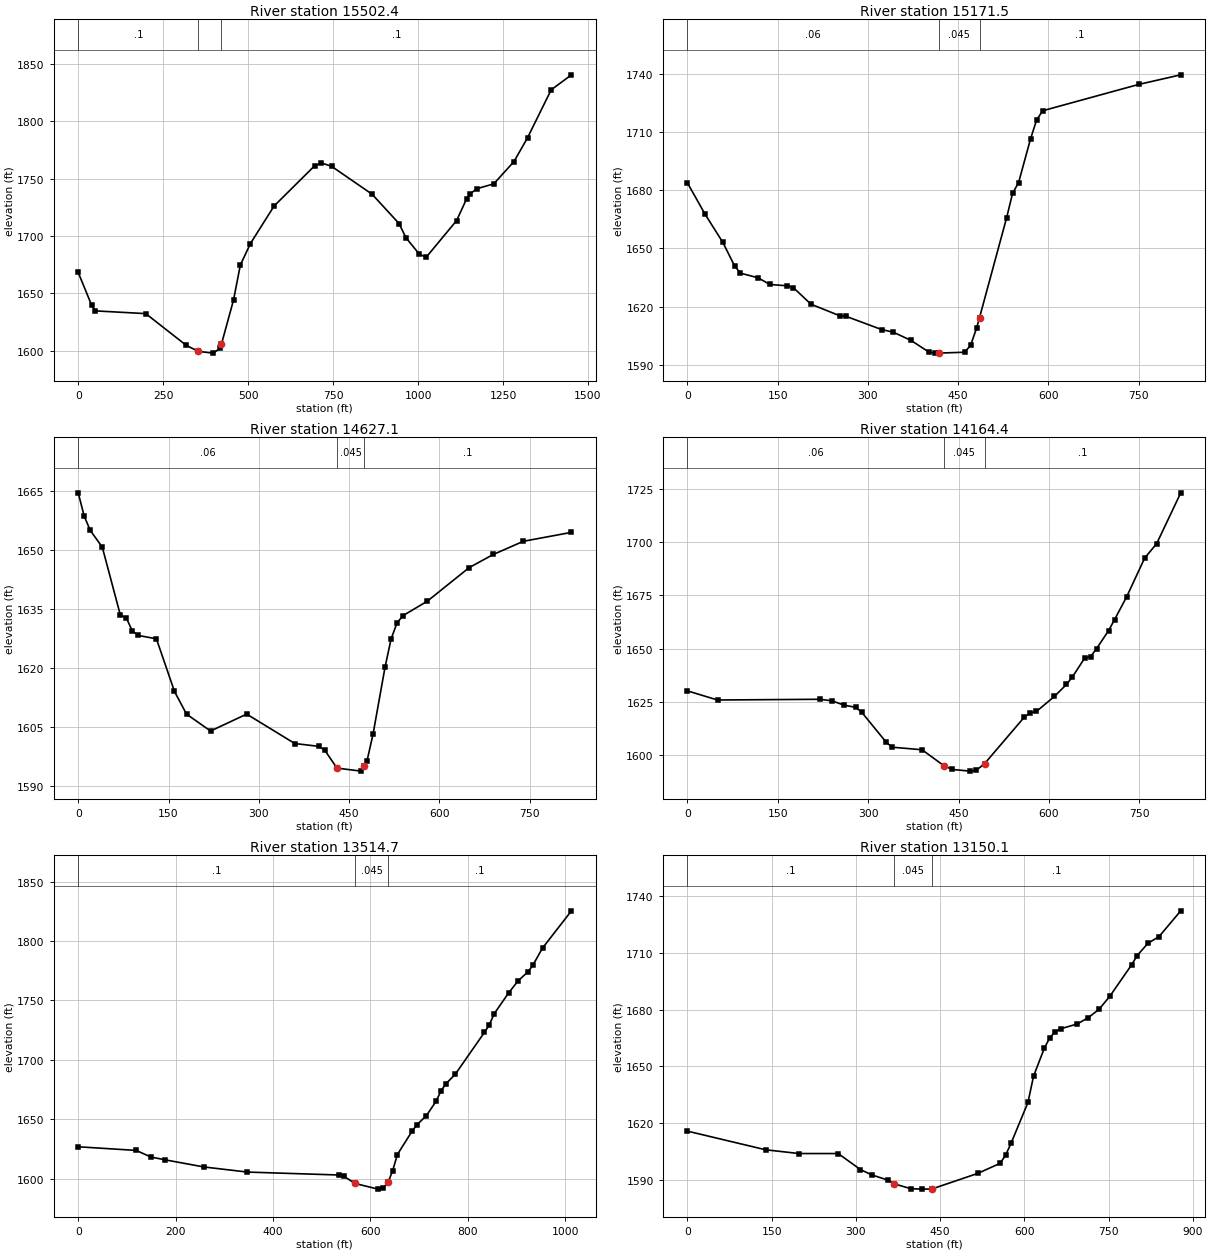
Type RM Length L Ch R = 1 ,15502.4 ,322.3,330.9,339.6
XS GIS Cut Line= 3
     2000975.118      127614.636     2000399.324       127141.37
     1999710.294      126987.333
#Sta/Elev= 30
       0 1668.14    39.8 1639.29    49.7 1634.58   198.8 1632.18     318 1604.49
   353.71599.201   397.5 1597.72   417.4 1601.92   421.41605.452   457.1 1644.14
     477 1674.52   506.8 1693.34   576.4 1726.05   695.6 1761.12   715.5 1763.62
   745.3  1760.7   864.7 1736.34   944.2 1710.68   964.1 1698.49  1003.9 1683.98
  1023.8 1681.32  1113.3  1713.3  1143.1 1732.49    1153 1736.57  1172.9 1741.14
  1222.6 1745.34  1282.3 1764.86  1322.1 1785.59  1391.7 1827.39  1451.4 1840.47
#Mann= 3 , 0 , 0
       0      .1       0   353.7    .045       0   421.4      .1       0
Bank Sta=353.7,421.4
XS Rating Curve= 0 ,0
Exp/Cntr=0.3,0.1

Type RM Length L Ch R = 1 ,15171.5 ,536.4,544.5,552.6
XS GIS Cut Line= 3
     2001138.844       127527.35     2000926.658      127175.742
      2000739.69      126811.648
#Sta/Elev= 30
       0 1683.69    29.3 1667.59    58.7 1653.16    78.2 1641.12      88 1637.31
   117.3 1634.92   136.9 1631.48   166.2 1630.79     176 1629.84   205.3 1621.34
   254.2 1615.24     264 1615.05   322.7 1608.29   342.2 1606.93   371.6  1602.7
   400.9 1596.79   410.7 1596.16   417.51596.174   460.6 1596.62   470.6 1600.12
   480.6 1609.05   485.5 1614.43   530.5 1665.78   540.4 1678.34   550.4 1683.91
   570.4  1706.5   580.4  1716.1   590.4 1720.85   750.1  1734.4     820 1739.34
#Mann= 3 , 0 , 0
       0     .06       0   417.5    .045       0   485.5      .1       0
Bank Sta=417.5,485.5
XS Rating Curve= 0 ,0
Exp/Cntr=0.3,0.1

Type RM Length L Ch R = 1 ,14627.1 ,455.3,462.6,469.8
XS GIS Cut Line= 3
     2001453.776      127420.552      2001420.15       127012.23
      2001383.08      126604.447
#Sta/Elev= 30
       0 1664.51      10 1658.57      20 1654.97      40 1650.72      70 1633.46
    79.9 1632.73    89.9 1629.42    99.9 1628.29   129.9 1627.43   159.9 1614.06
   179.9 1608.31   219.8 1604.02   279.8 1608.31   359.7 1600.84   399.7 1600.12
   409.7  1599.1   429.7  1594.6   469.6 1593.83   474.81595.172   479.6 1596.41
   489.6 1603.18   509.6 1620.26   519.6 1627.38   529.6 1631.52   539.5 1633.33
   579.5 1636.96   649.4 1645.53   689.3 1648.85   739.3  1652.2   819.2 1654.47
#Mann= 3 , 0 , 0
       0     .06       0   429.7    .045       0   474.8      .1       0
#XS Ineff= 2 , 0
           279.8 1608.31
Permanent Ineff=
       F       F
Bank Sta=429.7,474.8
XS Rating Curve= 0 ,0
Exp/Cntr=0.3,0.1

Type RM Length L Ch R = 1 ,14164.4 ,633.7,649.7,665.7
XS GIS Cut Line= 3
     2001756.373      127497.941     2001858.572      127101.397
     2001961.938      126705.158
#Sta/Elev= 30
       0 1630.12    49.9 1625.84   219.7 1626.18   239.7 1625.47   259.7 1623.46
   279.7 1622.36   289.6 1620.01   329.6 1606.13   339.6 1603.69   389.5 1602.48
   425.41595.063   439.5 1593.23   469.4 1592.45   479.4  1592.8   493.41595.994
   559.3 1617.81   569.3 1619.79   579.3 1620.45   609.3 1627.53   629.2 1633.14
   639.2 1636.72   659.2 1645.38   669.2  1646.2   679.2 1649.93   699.2 1658.44
   709.1 1663.58   729.1 1674.25   759.1 1692.48     779 1699.26     819 1723.11
#Mann= 3 , 0 , 0
       0     .06       0   425.4    .045       0   493.4      .1       0
Bank Sta=425.4,493.4
XS Rating Curve= 0 ,0
Exp/Cntr=0.3,0.1

Type RM Length L Ch R = 1 ,13514.7 ,351.6,364.6,377.4
XS GIS Cut Line= 2
     2001893.775      127706.142     2002753.174      127169.971
#Sta/Elev= 30
       0 1626.77   119.2 1623.71     149 1618.19   178.8 1615.76   258.2 1609.78
   347.6 1605.48   536.3    1603   546.2 1601.81   568.31595.911   615.7 1591.13
   625.6  1591.8   636.3 1596.89   645.5 1606.35   655.4 1620.24   685.2 1639.65
   695.2 1645.15     715 1652.99   734.9 1665.08   744.8 1673.68   754.7  1679.6
   774.6 1687.99   834.2 1723.08   844.1 1729.28     854 1738.61   883.8 1756.25
   903.7 1766.62   923.6 1774.01   933.5  1779.5   953.4 1794.02  1012.9 1825.36
#Mann= 3 , 0 , 0
       0      .1       0   568.3    .045       0   636.3      .1       0
Bank Sta=568.3,636.3
XS Rating Curve= 0 ,0
Exp/Cntr=0.3,0.1

Type RM Length L Ch R = 1 ,13150.1 ,595.8,563.5,531.3
XS GIS Cut Line= 3
     2002081.531       127699.81     2002697.605      127713.872
     2002929.462      127591.543
#Sta/Elev= 30
       0 1615.94   139.2 1606.12   198.8 1604.14   268.4 1604.14   308.1 1595.68
     328 1592.93   357.8 1590.04   367.21588.263   397.6 1585.63   417.4  1585.4
   435.21585.479   516.8 1593.67   556.6 1598.97   566.5 1603.26   576.5 1609.76
   606.3 1631.04   616.2 1644.82   635.6 1659.76   645.4 1665.18   655.1  1668.4
   664.8 1669.88   693.9 1672.37   713.3 1675.64   732.8 1680.07   752.2 1687.02
     791 1703.59   800.7  1708.4   820.1 1714.92   839.6 1718.37   878.4 1731.98
#Mann= 3 , 0 , 0
       0      .1       0   367.2    .045       0   435.2      .1       0
Bank Sta=367.2,435.2
XS Rating Curve= 0 ,0
Exp/Cntr=0.3,0.1