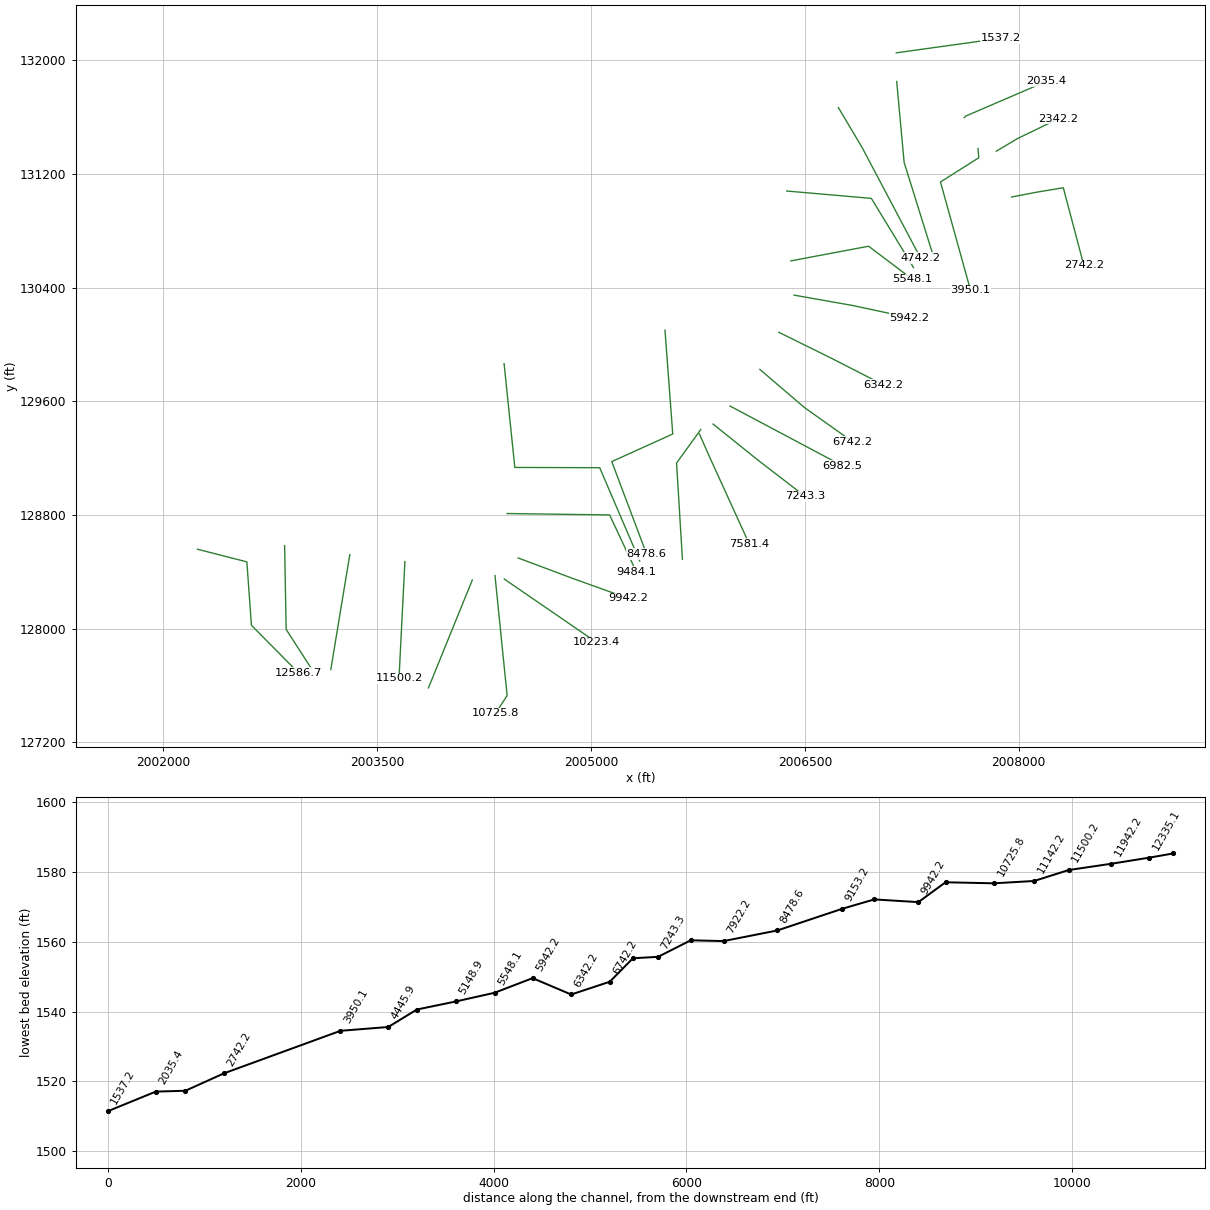
HEC-RAS study EastRiver2.prj: EastRiver2

--- EastRiver2.g01 (geometry) --- (continued)

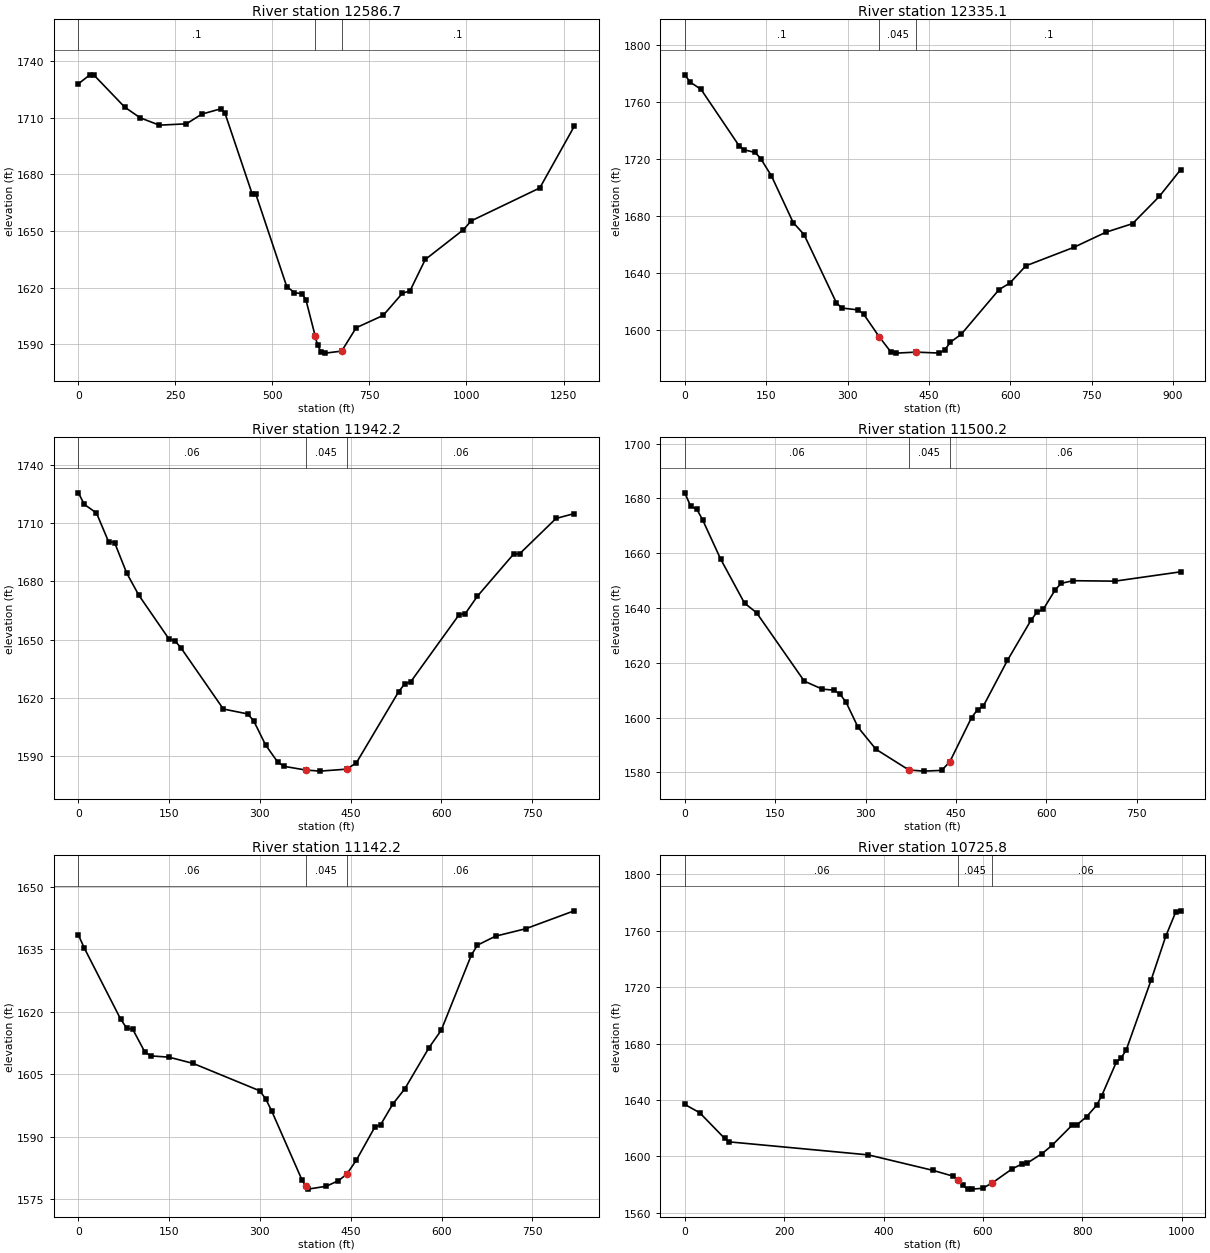
Type RM Length L Ch R = 1 ,12586.7 ,252.6,251.5,250.4
XS GIS Cut Line= 4
     2002239.654       128558.28     2002586.388      128469.179
     2002618.382      128023.037     2002949.813      127686.743
#Sta/Elev= 30
       0 1728.03    29.8 1732.81    39.8 1732.77   119.3 1715.72   159.1 1710.04
   208.8 1706.12   278.4 1706.83   318.2 1711.99   367.9 1714.84   377.9 1712.41
   447.5 1669.88   457.4 1669.48   536.9 1620.56   556.8 1617.35   576.7 1616.69
   586.6 1613.31   610.41594.196   616.4 1589.36   626.4 1585.65   636.3 1585.26
   678.41586.332   715.8 1598.71   785.4 1605.26   834.8 1616.97   854.5 1618.28
   893.8  1634.9   992.2  1650.7  1011.9 1655.35  1188.9 1672.84  1277.4 1705.43
#Mann= 3 , 0 , 0
       0      .1       0   610.4    .045       0   678.4      .1       0
Bank Sta=610.4,678.4
XS Rating Curve= 0 ,0
Exp/Cntr=0.3,0.1

Type RM Length L Ch R = 1 ,12335.1 ,396.7,392.9,389.1
XS GIS Cut Line= 3
     2002851.191      128583.412      2002861.85      127994.053
     2003037.268      127720.766
#Sta/Elev= 30
       0 1778.96      10 1773.85      30 1768.75    99.9 1729.37   109.9  1726.4
   129.9 1724.56   139.9 1720.32   159.8 1708.15   199.8 1675.52   219.8 1667.12
   279.7 1619.15   289.7 1615.61   319.7 1614.32   329.7 1611.37   358.6 1595.41
   379.6 1585.02   389.6 1584.04   426.61584.746   469.6 1584.08   479.6 1586.39
   489.6  1591.7   509.5 1597.17   579.5 1628.56   599.3 1633.08   628.8 1645.18
   717.4 1658.15   776.4 1668.71   825.6 1674.74   874.8 1693.75   914.2 1712.52
#Mann= 3 , 0 , 0
       0      .1       0   358.6    .045       0   426.6      .1       0
Bank Sta=358.6,426.6
XS Rating Curve= 0 ,0
Exp/Cntr=0.3,0.1

Type RM Length L Ch R = 1 ,11942.2 ,439.5,441.9,444.4
XS GIS Cut Line= 3
     2003308.273      128519.424      2003241.59      128115.528
     2003175.066      127711.065
#Sta/Elev= 30
       0  1725.6      10 1719.61      30 1715.21    49.9 1700.47    59.9    1700
    79.9  1684.3    99.8 1672.96   149.8 1650.32   159.8 1649.34   169.7 1645.71
   239.6 1614.28   279.6 1611.77   289.6 1608.29   309.5 1595.73   329.5 1586.94
   339.5 1584.79   375.41582.878   399.4  1582.3   443.4 1583.32   459.4 1586.55
   529.3 1623.21   539.3  1627.2   549.3 1628.31   629.3  1662.9   639.3 1663.37
   659.3 1672.32   719.3 1694.07   729.3 1694.23   789.3  1712.4   819.3 1714.91
#Mann= 3 , 0 , 0
       0     .06       0   375.4    .045       0   443.4     .06       0
Bank Sta=375.4,443.4
XS Rating Curve= 0 ,0
Exp/Cntr=0.3,0.1

Type RM Length L Ch R = 1 ,11500.2 ,365.1,358,351
XS GIS Cut Line= 2
     2003694.664      128471.327     2003653.382      127649.499
#Sta/Elev= 30
       0 1682.07     9.9 1677.08    19.8 1676.16    29.7 1672.15    59.5 1657.89
    99.1 1641.81     119 1638.34   198.3 1613.34     228 1610.44   247.8 1610.04
   257.8 1608.54   267.7 1605.63   287.5 1596.51   317.2 1588.49   371.91580.911
   396.6  1580.5   426.3 1580.77   439.91583.934   475.9 1600.04   485.8 1602.91
   495.7 1604.34   535.4 1620.89     575 1635.74   584.9 1638.59   594.8 1639.52
   614.7 1646.64   624.6 1649.03   644.4    1650   713.8 1649.83   822.9 1653.24
#Mann= 3 , 0 , 0
       0     .06       0   371.9    .045       0   439.9     .06       0
Bank Sta=371.9,439.9
XS Rating Curve= 0 ,0
Exp/Cntr=0.3,0.1

Type RM Length L Ch R = 1 ,11142.2 ,405.8,416.4,426.9
XS GIS Cut Line= 3
     2004167.422      128341.428     2004013.507      127961.951
      2003859.94      127582.339
#Sta/Elev= 30
       0  1638.5      10 1635.28    69.9 1618.23    79.9 1616.07    89.9 1615.79
   109.9 1610.32   119.8  1609.4   149.8 1609.09   189.8 1607.58   299.6 1601.01
   309.6 1599.04   319.6 1596.08   369.6 1579.52   375.51578.239   379.5 1577.37
   409.5 1578.06   429.5 1579.39   443.51580.967   459.4 1584.38   489.4 1592.19
   499.4 1592.87   519.4 1597.81   539.3 1601.49   579.3 1611.39   599.3 1615.53
   649.2 1633.64   659.2 1636.02   689.2 1638.18   739.1 1639.97     819 1644.27
#Mann= 3 , 0 , 0
       0     .06       0   375.5    .045       0   443.5     .06       0
Bank Sta=375.5,443.5
XS Rating Curve= 0 ,0
Exp/Cntr=0.3,0.1

Type RM Length L Ch R = 1 ,10725.8 ,483,502.4,521.8
XS GIS Cut Line= 3
     2004326.521       128372.78     2004411.541      127528.372
     2004330.911      127402.872
#Sta/Elev= 30
       0 1636.78      30 1630.89    79.9 1612.79    89.9 1610.21   369.4 1600.99
   499.2 1590.02   539.2 1585.96   549.91583.243   559.1 1579.37   569.1 1576.74
   577.9  1576.7   599.1  1577.3   617.91580.898     659 1591.13   678.9 1594.59
   688.9 1595.14   718.9 1601.89   738.8 1607.68   778.8 1621.86   788.8 1622.23
   808.7 1628.13   828.7 1636.16   838.7 1642.68   868.6 1666.97   878.5 1669.93
   888.5 1675.61   938.2 1724.81     968 1756.19   987.9 1773.24   997.8 1774.12
#Mann= 3 , 0 , 0
       0     .06       0   549.9    .045       0   617.9     .06       0
Bank Sta=549.9,617.9
XS Rating Curve= 0 ,0
Exp/Cntr=0.3,0.1

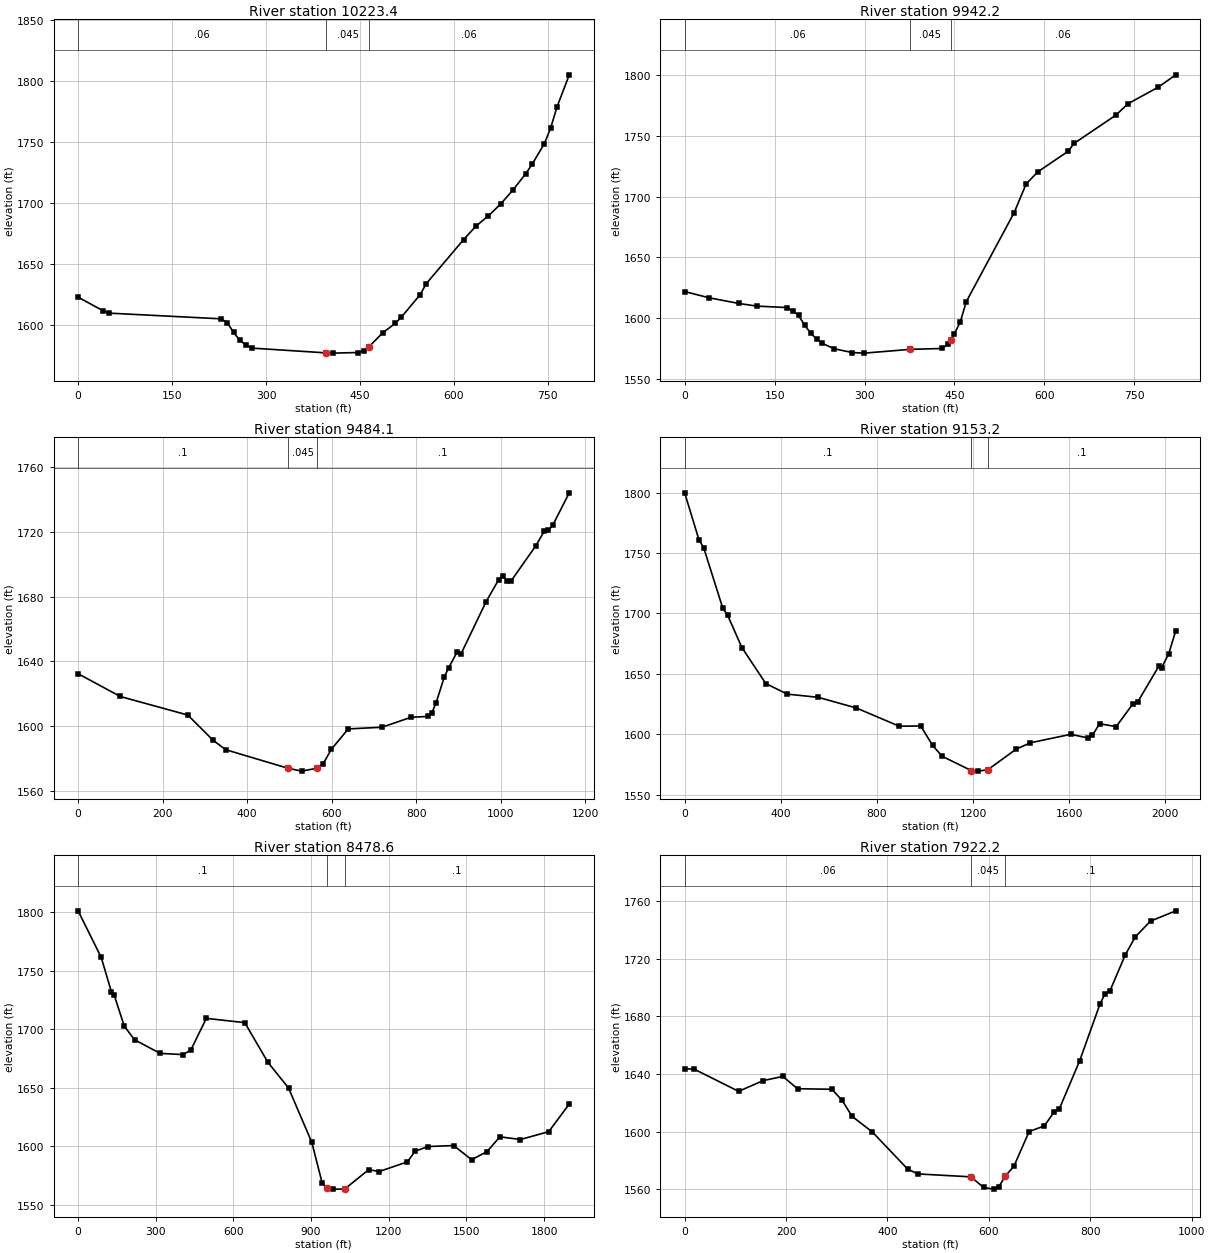
Type RM Length L Ch R = 1 ,10223.4 ,276.1,281.3,286.7
XS GIS Cut Line= 2
     2004391.767       128348.14     2005037.601      127903.235
#Sta/Elev= 30
       0 1622.92    39.7 1611.79    49.6 1609.81   228.3 1605.14   238.2  1602.1
   248.2    1594   258.1 1587.65     268 1583.53     278  1581.1   396.41577.191
     407    1577   446.7  1577.5   456.6 1578.96   464.41582.189   486.4  1593.7
   506.3 1601.38   516.2 1606.58     546 1624.87   555.9 1633.99   615.5 1670.16
   635.3 1681.22   655.2  1689.7     675 1699.52   694.9  1711.2   714.8 1724.32
   724.7 1731.77   744.5 1748.97   754.5  1761.7   764.4  1778.7   784.2 1805.34
#Mann= 3 , 0 , 0
       0     .06       0   396.4    .045       0   464.4     .06       0
Bank Sta=396.4,464.4
XS Rating Curve= 0 ,0
Exp/Cntr=0.3,0.1

Type RM Length L Ch R = 1 ,9942.2  ,450.7,458,465
XS GIS Cut Line= 3
     2004489.313       128496.65     2004872.791       128352.22
     2005258.038       128213.53
#Sta/Elev= 30
       0 1621.98      40 1616.91      90 1612.21   119.9    1610   169.9 1608.82
   179.9 1606.37   189.9 1602.35   199.9 1594.45   209.9 1587.94   219.9 1582.94
   229.9 1579.27   249.9 1574.85   279.8 1571.77   299.8 1571.32   375.81574.412
   429.8 1575.14   439.7 1579.05   443.81582.326   449.7 1587.04   459.7 1596.96
   469.7 1613.62   549.6 1686.91   569.6 1710.54   589.5  1720.6   639.5 1737.27
   649.4 1743.78   719.4 1767.11   739.3 1776.39   789.3 1789.89   819.2 1800.21
#Mann= 3 , 0 , 0
       0     .06       0   375.8    .045       0   443.8     .06       0
Bank Sta=375.8,443.8
XS Rating Curve= 0 ,0
Exp/Cntr=0.3,0.1

Type RM Length L Ch R = 1 ,9484.1  ,330.7,330.9,331.1
XS GIS Cut Line= 3
     2004411.541      128809.477     2005130.351      128799.815
     2005318.053      128398.467
#Sta/Elev= 30
       0 1632.31    99.8 1618.23   259.6 1606.75   319.5 1591.12   349.4 1585.32
   497.41573.803   529.2 1572.09   565.41573.895   579.1 1576.35   599.1 1585.55
     639 1598.18   718.9 1599.22   787.8 1605.38   827.2  1605.9     837 1608.17
   846.9 1614.31   866.6 1630.46   876.4 1635.86   896.1 1645.45     906 1644.59
     965 1676.71   994.6 1690.26  1004.4 1693.02  1014.3 1689.64  1024.1 1689.55
  1083.2 1711.51  1102.9 1720.47  1112.7 1720.98  1122.6 1723.95    1162 1744.13
#Mann= 3 , 0 , 0
       0      .1       0   497.4    .045       0   565.4      .1       0
Bank Sta=497.4,565.4
XS Rating Curve= 0 ,0
Exp/Cntr=0.3,0.1

Type RM Length L Ch R = 1 ,9153.2  ,732.7,674.6,616.5
XS GIS Cut Line= 4
     2004390.286      129864.504      2004465.65      129133.903
     2005060.789      129132.168     2005341.534      128475.108
#Sta/Elev= 30
       0 1799.87    59.6 1760.93    79.4 1754.29   158.8 1704.24   178.7 1698.53
   238.2 1671.76   337.5 1641.98   426.8 1633.19   555.8 1630.54   714.6  1621.7
   893.2  1606.6   982.4 1606.84    1032 1590.69  1071.7 1581.71  1193.61569.803
  1220.5 1569.42  1261.61570.535  1379.2 1587.57  1438.8 1592.89  1607.5 1599.91
    1677 1596.92  1696.8 1598.94  1726.6 1608.64    1796 1606.28  1865.5 1625.15
  1885.4 1626.68  1974.7 1656.76  1984.6 1654.91  2014.4 1666.48  2044.1 1685.84
#Mann= 3 , 0 , 0
       0      .1       0  1193.6    .045       0  1261.6      .1       0
Bank Sta=1193.6,1261.6
XS Rating Curve= 0 ,0
Exp/Cntr=0.3,0.1

Type RM Length L Ch R = 1 ,8478.6  ,530.3,556.4,582.5
XS GIS Cut Line= 4
      2005518.74      130100.242     2005573.085      129369.235
     2005145.568       129175.04     2005389.599      128524.747
#Sta/Elev= 30
       0 1801.17    89.2 1761.39   128.8 1731.79   138.7 1729.61   178.3 1702.59
   217.9 1690.94     317 1679.28   406.1 1678.22   435.8  1682.3   495.3 1709.22
   643.9 1705.55     733  1671.7     813 1649.62   902.9 1603.11   942.8 1568.39
   961.41564.111   982.8  1563.2  1029.41563.227  1122.7 1579.87  1162.6  1578.2
    1272 1586.53  1301.8  1595.6  1351.4 1599.61  1450.6 1600.48  1520.1 1588.37
  1579.6  1595.3  1629.2 1607.94  1708.6 1605.63  1817.8 1612.32  1897.2 1635.99
#Mann= 3 , 0 , 0
       0      .1       0   961.4    .045       0  1029.4      .1       0
Bank Sta=961.4,1029.4
XS Rating Curve= 0 ,0
Exp/Cntr=0.3,0.1

Type RM Length L Ch R = 1 ,7922.2  ,332.9,340.6,348.3
XS GIS Cut Line= 3
     2005769.612      129400.566     2005599.896      129165.017
     2005641.034      128487.833
#Sta/Elev= 30
       0 1643.73    19.4 1643.22   106.4 1627.94   154.8 1635.37   193.6 1638.28
   222.6 1629.75   290.3 1629.38   310.3 1621.86   330.2 1610.61   370.1 1599.81
     440 1574.01   459.9  1570.7   564.61568.687   589.6 1561.32   609.6 1560.17
   619.6 1561.78   632.61569.279   649.5 1576.01   679.4 1600.06   709.4 1603.98
   729.3 1613.91   739.3    1616   779.2 1649.19   819.1 1688.29   829.1 1695.58
     839 1697.68     869 1722.45   888.9 1735.04   918.9 1745.93   968.8 1753.05
#Mann= 3 , 0 , 0
       0     .06       0   564.6    .045       0   632.6      .1       0
Bank Sta=564.6,632.6
XS Rating Curve= 0 ,0
Exp/Cntr=0.3,0.1

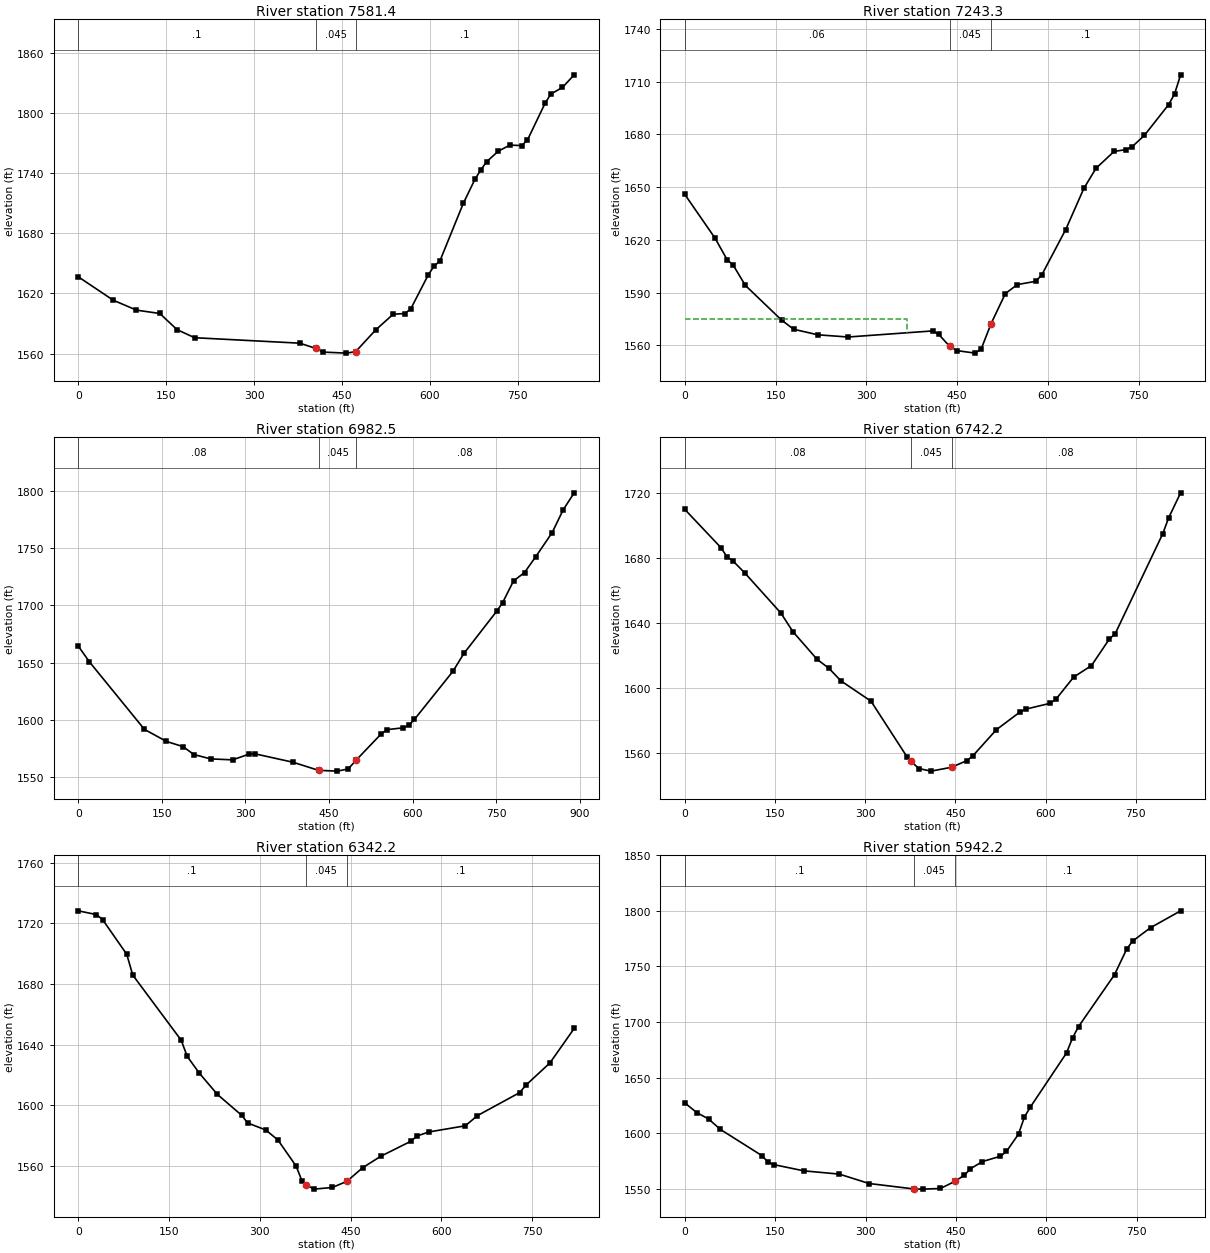
Type RM Length L Ch R = 1 ,7581.4  ,327.9,338.3,348.7
XS GIS Cut Line= 3
     2005760.275      129369.839     2005827.905      129215.256
     2006108.456      128598.487
#Sta/Elev= 30
       0  1636.5    59.6 1613.19    99.2  1603.3     139 1599.95   168.7 1583.74
   198.6 1575.77     378 1570.32   405.41565.093   417.8 1561.44   457.7 1560.39
   473.41561.909   507.5 1583.52   537.4 1599.21   557.3 1599.92   567.3 1604.47
   597.2 1638.35   607.2 1647.23   617.1 1652.32     657 1709.73   676.9 1733.77
   686.9  1743.2   696.8 1751.29   716.8 1761.93   736.7 1767.96   756.6  1767.5
   766.6 1773.04   796.5 1809.54   806.4 1818.88   826.4 1825.54   846.3 1838.09
#Mann= 3 , 0 , 0
       0      .1       0   405.4    .045       0   473.4      .1       0
Bank Sta=405.4,473.4
XS Rating Curve= 0 ,0
Exp/Cntr=0.3,0.1

Type RM Length L Ch R = 1 ,7243.3  ,257.4,260.9,264.3
XS GIS Cut Line= 3
     2005856.003      129439.332     2006174.854      129182.196
     2006499.073      128932.084
#Sta/Elev= 30
       0 1645.92      50 1621.03    69.9  1608.8    79.9 1605.74    99.9 1594.23
   159.8 1574.46   179.8 1569.24   219.8 1566.07   269.8 1564.83   409.6 1568.29
   419.6 1566.27   437.81559.434   449.6 1557.09   479.5 1555.66   489.5 1557.88
   505.81572.292   529.5  1589.5   549.4 1594.65   579.4 1596.48   589.4 1599.94
   629.3 1625.96   659.3 1649.39   679.3 1660.76   709.2 1670.37   729.2 1671.41
   739.2  1673.1   759.2 1679.48   799.1  1696.9   809.1 1703.07   819.1 1713.93
#Mann= 3 , 0 , 0
       0     .06       0   437.8    .045       0   505.8      .1       0
#XS Ineff= 2 , 0
          367.06 1574.88
Permanent Ineff=
       F       F
Bank Sta=437.8,505.8
XS Rating Curve= 0 ,0
Exp/Cntr=0.3,0.1

Type RM Length L Ch R = 1 ,6982.5  ,245,240.3,237.4
XS GIS Cut Line= 2
     2005974.517      129566.328     2006759.991      129147.505
#Sta/Elev= 30
       0 1664.39    19.8 1650.74   118.7 1591.68   158.2  1581.2   187.9 1576.64
   207.7  1569.7   237.4 1565.94   276.9 1565.09   306.6 1570.11   316.5 1570.42
   385.7 1562.98   431.31555.934   464.9 1555.25   484.6 1557.16   499.31565.128
     544 1587.87   553.9 1591.46   583.6 1593.09   593.4 1595.27   603.3 1600.34
   672.6 1642.43   692.3 1658.05   751.7 1695.24   761.6 1702.21   781.4 1721.36
   801.1 1728.67   820.9 1742.26   850.6 1763.43   870.4 1783.33   890.2 1798.26
#Mann= 3 , 0 , 0
       0     .08       0   431.3    .045       0   499.3     .08       0
#XS Ineff= 2 , 0
           314.5 1570.17
Permanent Ineff=
       F       F
Bank Sta=431.3,499.3
XS Rating Curve= 0 ,0
Exp/Cntr=0.3,0.1

Type RM Length L Ch R = 1 ,6742.2  ,394.6,400,403.2
XS GIS Cut Line= 3
     2006183.999      129823.958       2006494.6      129557.268
     2006832.363      129316.311
#Sta/Elev= 30
       0  1709.7    59.9 1686.24    69.9 1680.64    79.9 1678.03    99.8 1670.54
   159.8 1645.85   179.7 1634.43   219.7 1617.46   239.6 1611.86   259.6  1604.1
   309.5 1591.63   369.4 1557.35   375.41554.656   389.4  1550.1   409.4 1548.53
   443.4  1550.9   468.7 1554.96   478.5  1557.8     518 1574.04   557.6 1585.03
   567.4 1586.75     607 1590.26   616.8 1592.69   646.5 1606.45   676.1 1613.53
   705.7 1629.82   715.6 1633.22   794.6 1694.72   804.5 1704.61   824.3 1719.91
#Mann= 3 , 0 , 0
       0     .08       0   375.4    .045       0   443.4     .08       0
Bank Sta=375.4,443.4
XS Rating Curve= 0 ,0
Exp/Cntr=0.3,0.1

Type RM Length L Ch R = 1 ,6342.2  ,394,400,405.5
XS GIS Cut Line= 3
     2006317.382      130085.137     2006684.484      129903.175
     2007048.773      129716.267
#Sta/Elev= 30
       0 1728.18      30 1725.68      40 1722.44      80 1699.56    89.9 1685.88
   169.9 1642.97   179.9  1632.3   199.9 1621.27   229.8 1607.24   269.8 1593.54
   279.8 1588.45   309.8 1583.82   329.8 1577.21   359.8 1560.07   369.8    1550
   375.71547.729   389.7 1544.88   419.7 1545.97   443.71550.022   469.6 1558.94
   499.6 1566.51   549.5 1576.42   559.5 1579.87   579.5 1582.56   639.4  1586.6
   659.4  1593.3   729.3 1608.48   739.3 1613.28   779.2 1628.02   819.2 1650.68
#Mann= 3 , 0 , 0
       0      .1       0   375.7    .045       0   443.7      .1       0
Bank Sta=375.7,443.7
XS Rating Curve= 0 ,0
Exp/Cntr=0.3,0.1

Type RM Length L Ch R = 1 ,5942.2  ,386.3,394,402.4
XS GIS Cut Line= 3
     2006424.085      130346.775     2006832.033      130274.337
      2007231.61      130188.713
#Sta/Elev= 30
       0 1627.19    19.7 1618.54    39.5 1612.68    59.2 1603.27   128.2 1579.65
   138.1 1573.82     148  1571.6   197.3 1566.04   256.5 1563.08   305.8 1554.62
   380.3 1549.72   394.6 1549.56   424.3 1550.13   448.31556.543   464.2 1562.16
   474.1 1567.89   494.1 1574.39     524 1579.18   533.9 1583.47   553.9 1599.09
   563.8 1614.56   573.8 1623.62   633.6 1672.15   643.6  1685.7   653.5 1695.86
   713.3 1742.63   733.3 1765.47   743.2 1772.82   773.1 1784.94     823  1800.1
#Mann= 3 , 0 , 0
       0      .1       0   380.3    .045       0   448.3      .1       0
Bank Sta=380.3,448.3
XS Rating Curve= 0 ,0
Exp/Cntr=0.3,0.1

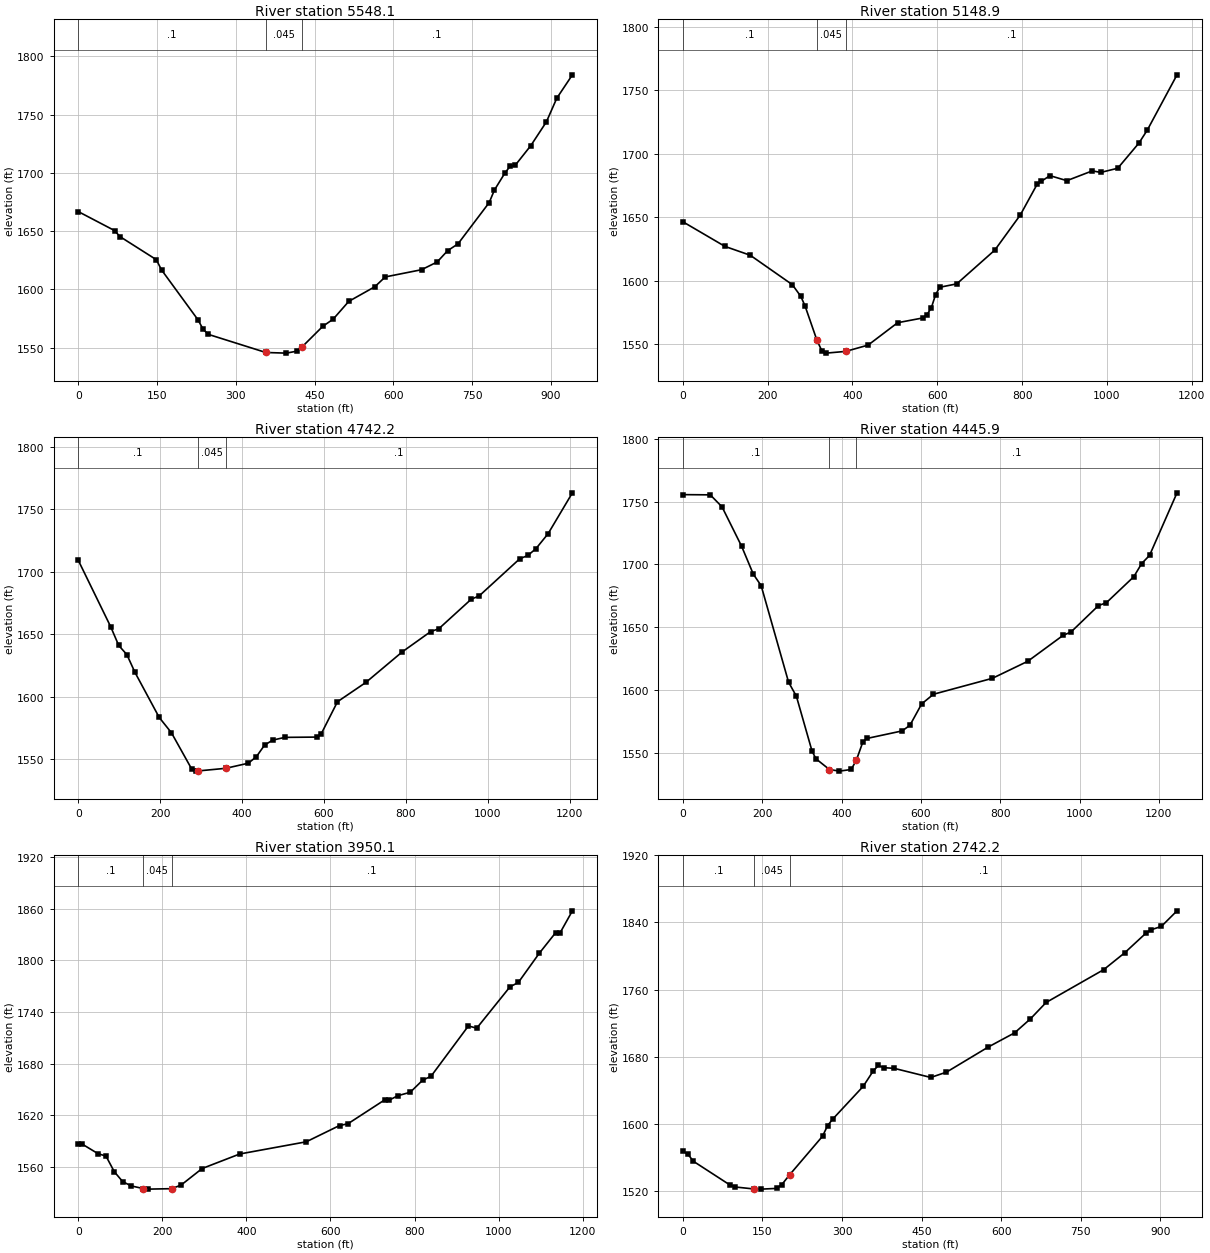
Type RM Length L Ch R = 1 ,5548.1  ,405.2,399.3,393.5
XS GIS Cut Line= 3
     2006401.899      130588.028     2006946.939      130690.917
     2007254.471      130457.624
#Sta/Elev= 30
       0 1666.88    69.3 1650.53    79.2 1645.46   148.6  1625.6   158.5 1616.84
   227.8 1574.06   237.7  1565.9   247.6 1561.48   357.21545.919   396.2 1545.38
     416 1547.06   425.21550.331   465.5 1568.38   485.3 1574.54     515  1589.8
   564.6 1602.36   584.4 1610.78   653.6 1616.98   683.3 1623.62   703.1 1633.28
   722.9 1639.15   782.3 1674.58   792.2 1685.31     812 1699.79   821.9  1705.7
   831.8 1706.58   861.5 1723.47   891.2 1743.88     911  1764.2   940.7 1784.25
#Mann= 3 , 0 , 0
       0      .1       0   357.2    .045       0   425.2      .1       0
Bank Sta=357.2,425.2
XS Rating Curve= 0 ,0
Exp/Cntr=0.3,0.1

Type RM Length L Ch R = 1 ,5148.9  ,427.6,406.6,384.7
XS GIS Cut Line= 3
     2006372.381      131079.558     2006966.021      131027.739
     2007261.631      130540.917
#Sta/Elev= 30
       0 1646.47    99.3 1627.04   158.9 1620.08   258.2 1596.87   278.1 1587.69
     288 1580.23   316.21553.043   327.7 1544.77   337.7  1542.9   384.21544.269
     437 1549.25   506.5 1566.88   566.1 1570.65     576 1573.35     586 1578.66
   595.9 1588.93   605.9 1594.83   645.9 1597.51   735.8 1624.17   795.7 1651.75
   835.7 1676.17   845.7 1678.45   865.7 1682.84   905.6 1678.88   965.6  1686.6
   985.6 1685.38  1025.6 1688.68  1075.5 1708.48  1095.5 1718.87  1165.4 1762.33
#Mann= 3 , 0 , 0
       0      .1       0   316.2    .045       0   384.2      .1       0
Bank Sta=316.2,384.2
XS Rating Curve= 0 ,0
Exp/Cntr=0.3,0.1

Type RM Length L Ch R = 1 ,4742.2  ,305.8,296.2,287.7
XS GIS Cut Line= 3
     2006734.377      131667.402     2006900.746      131386.584
       2007311.1      130607.627
#Sta/Elev= 30
       0 1709.33    79.1 1656.21    98.9 1641.12   118.7 1633.85   138.5  1619.6
   197.8  1583.5   227.5 1571.33     277 1542.29   286.8 1540.58   292.41540.721
   360.41542.841   415.4 1546.92   435.2  1552.2     455 1561.39   474.8 1565.39
   504.5 1567.59   583.6 1567.83   593.5 1570.48   633.1 1596.12   702.3 1611.53
   791.4 1636.04   860.6 1652.22   880.4 1654.48   959.5 1678.09   979.3 1680.84
  1078.2 1710.51    1098 1713.15  1117.8 1718.62  1147.5  1730.6  1206.8 1763.29
#Mann= 3 , 0 , 0
       0      .1       0   292.4    .045       0   360.4      .1       0
Bank Sta=292.4,360.4
XS Rating Curve= 0 ,0
Exp/Cntr=0.3,0.1

Type RM Length L Ch R = 1 ,4445.9  ,518.9,495.8,472.6
XS GIS Cut Line= 3
     2007143.791      131850.891     2007195.962      131280.868
     2007395.805      130637.781
#Sta/Elev= 30
       0 1755.57    69.1 1755.39    98.7 1745.84     148 1714.56   177.6 1692.28
   197.4 1683.11   266.5 1606.35   286.2 1595.14   325.7 1551.46   335.6 1545.38
   369.51536.849   394.8 1535.58   424.4 1536.89   437.51544.407     454 1558.98
   463.8 1561.56   552.7 1567.57   572.4 1572.02   602.1 1589.09   631.8 1596.75
   780.4 1609.43   869.5 1622.97   958.6 1643.61   978.4 1646.23  1047.8  1667.3
  1067.6 1669.55  1136.9 1690.28  1156.7 1700.74  1176.5  1707.2  1245.8    1757
#Mann= 3 , 0 , 0
       0      .1       0   369.5    .045       0   437.5      .1       0
Bank Sta=369.5,437.5
XS Rating Curve= 0 ,0
Exp/Cntr=0.3,0.1

Type RM Length L Ch R = 1 ,3950.1  ,1147.9,1207.9,1267.4
XS GIS Cut Line= 4
     2007713.815      131379.414     2007719.611      131313.717
     2007450.915      131143.274     2007661.643      130380.423
#Sta/Elev= 30
       0 1586.36     9.4 1586.74    47.1 1575.62      66 1572.83    85.8 1554.67
   105.7 1543.23   125.6 1538.27   154.31535.181   165.4 1534.49   222.31535.013
   244.9 1539.29   294.7 1558.39   384.2 1575.28   542.4 1589.41   621.6 1608.31
   641.4 1610.29   730.4 1638.51   740.3 1637.88   760.1 1642.88   789.8 1646.91
   819.4 1660.97   839.2 1665.44   928.2 1723.89     948 1721.27  1027.2 1769.31
    1047 1774.33  1096.4 1807.96    1136 1832.28  1145.9 1831.57  1175.6 1857.48
#Mann= 3 , 0 , 0
       0      .1       0   154.3    .045       0   222.3      .1       0
Bank Sta=154.3,222.3
XS Rating Curve= 0 ,0
Exp/Cntr=0.3,0.1

Type RM Length L Ch R = 1 ,2742.2  ,392.7,400,406.1
XS GIS Cut Line= 4
     2007949.553        131037.4     2008113.819      131069.406
     2008312.281      131102.483     2008455.812      130558.194
#Sta/Elev= 30
       0 1567.73     9.8 1563.73    19.7 1555.53    88.6 1527.31    98.4 1524.89
   133.41522.542   147.7 1522.32   176.9 1523.18   186.5 1527.72   201.41539.515
   263.2 1585.28   272.8 1597.97   282.3  1605.6   339.8 1644.64     359  1663.2
   368.6 1669.61   378.4 1666.95   398.2 1666.17   467.3 1655.31   496.9 1661.65
   575.9 1691.65   625.3 1708.44   654.9 1724.97   684.6 1744.57   793.2 1783.68
   832.7  1803.7   872.2 1826.79   882.1 1831.12   901.8 1835.12   931.4 1853.74
#Mann= 3 , 0 , 0
       0      .1       0   133.4    .045       0   201.4      .1       0
Bank Sta=133.4,201.4
XS Rating Curve= 0 ,0
Exp/Cntr=0.3,0.1

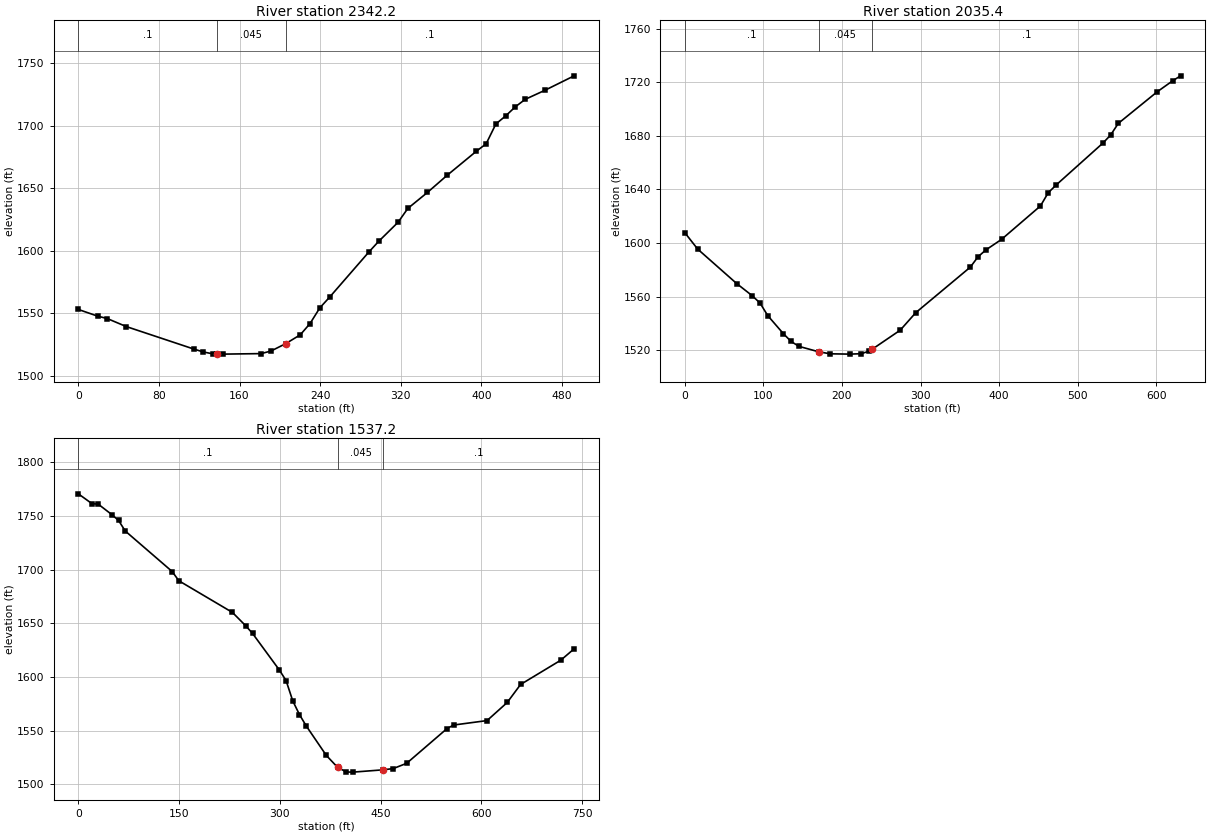
Type RM Length L Ch R = 1 ,2342.2  ,309.6,306.8,305.8
XS GIS Cut Line= 3
     2007842.311      131359.769     2007989.755       131447.94
     2008277.776      131588.258
#Sta/Elev= 30
       0 1553.07    19.1 1547.73    28.6 1545.81    47.7 1539.35   114.5 1521.43
   124.1 1519.06   133.6 1517.54   137.81517.448   143.2 1517.33   181.5 1517.75
   191.2  1519.8   205.81525.687   220.3 1532.77     230 1541.78   239.8 1554.41
   249.5 1562.94   288.3  1598.9     298 1607.41   317.4 1622.79   327.1 1633.87
   346.6 1646.67     366 1660.28   395.1 1679.59   404.8 1685.52   414.5 1701.41
   424.2 1707.86   433.9 1715.19   443.6  1721.1     463 1728.28   492.2 1739.91
#Mann= 3 , 0 , 0
       0      .1       0   137.8    .045       0   205.8      .1       0
Bank Sta=137.8,205.8
XS Rating Curve= 0 ,0
Exp/Cntr=0.3,0.1

Type RM Length L Ch R = 1 ,2035.4  ,503.9,498.2,492.3
XS GIS Cut Line= 3
       2007617.2       131595.83     2007628.794      131607.424
     2008193.021      131850.891
#Sta/Elev= 30
       0 1607.77    16.4 1595.48      66 1569.78    85.8 1560.68    95.7 1555.23
   105.6 1545.79   125.4 1532.38   135.3 1526.53   145.2  1522.9   170.2 1518.86
   184.9 1517.33   210.2 1517.09   224.5 1517.41   234.4 1519.29   238.21520.639
   274.1 1534.96   293.9 1548.04   363.3 1582.02   373.2  1589.8   383.1 1594.86
     403 1602.73   452.5 1627.67   462.4 1637.51   472.3 1643.22   531.8  1674.5
   541.7 1680.53   551.6 1689.32   601.2 1712.95     621  1721.2   630.9 1724.82
#Mann= 3 , 0 , 0
       0      .1       0   170.2    .045       0   238.2      .1       0
Bank Sta=170.2,238.2
XS Rating Curve= 0 ,0
Exp/Cntr=0.3,0.1

Type RM Length L Ch R = 1 ,1537.2  ,391.1,394.9,399.1
XS GIS Cut Line= 2
     2007141.024      132052.223     2007872.262       132154.26
#Sta/Elev= 30
       0 1770.61      20  1761.6    29.9 1760.88    49.9 1751.25    59.9 1745.84
    69.8 1736.02   139.7 1698.28   149.7 1689.64   229.5 1660.16   249.4 1647.64
   259.4 1640.62   299.3 1606.59   309.3 1596.76   319.3 1577.79   329.2 1565.12
   339.2 1554.62   369.2 1527.08   386.11515.876   399.1  1511.6   409.1 1511.47
   454.1 1513.63   468.9 1514.78   488.9 1519.68   548.8 1551.92   558.7 1555.31
   608.6 1559.47   638.6 1576.31   658.5 1593.08   718.4  1615.7   738.3  1626.3
#Mann= 3 , 0 , 0
       0      .1       0   386.1    .045       0   454.1      .1       0
Bank Sta=386.1,454.1
XS Rating Curve= 0 ,0
Exp/Cntr=0.3,0.1