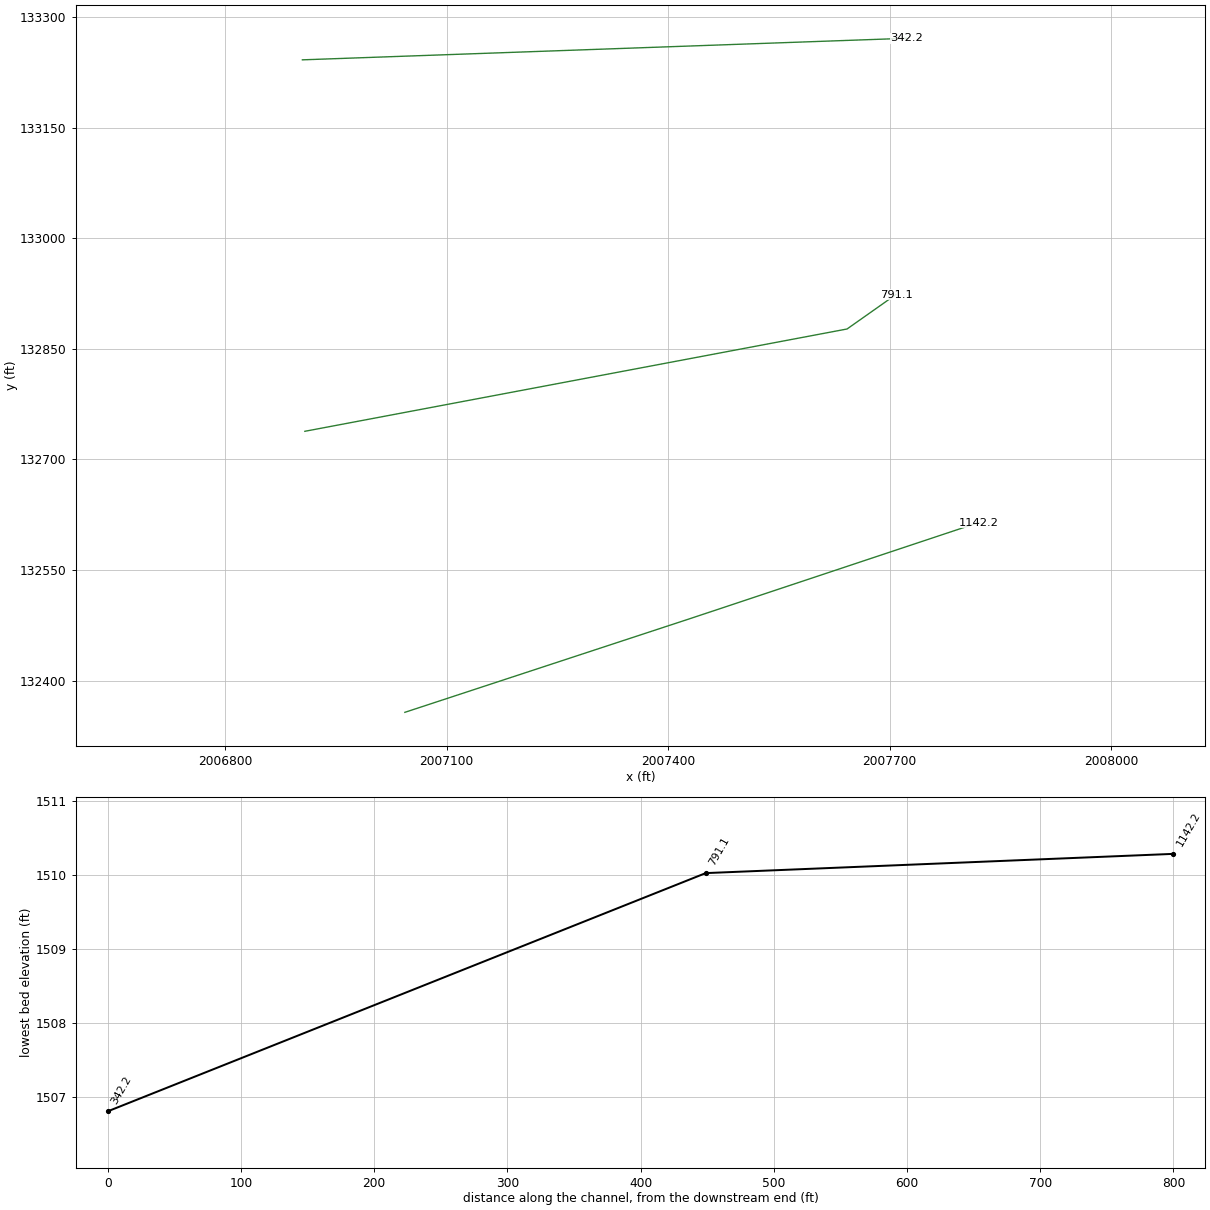
HEC-RAS study EastRiver2.prj: EastRiver2

--- EastRiver2.g01 (geometry) --- (continued)

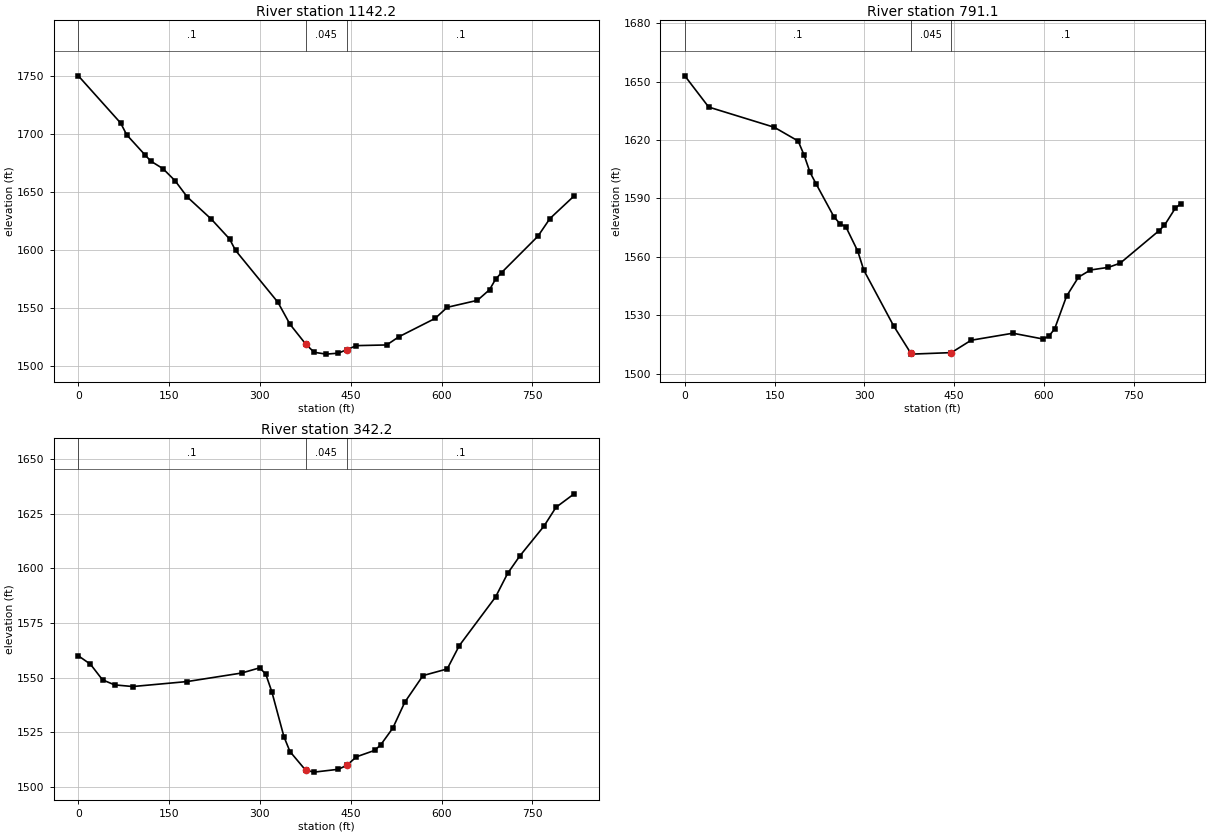
Type RM Length L Ch R = 1 ,1142.2  ,353.9,351.1,348.2
XS GIS Cut Line= 3
     2007043.339      132356.963     2007432.331      132484.942
     2007820.817      132614.436
#Sta/Elev= 30
       0 1750.47    69.9 1709.71    79.9 1699.56   109.9 1682.35   119.8 1676.83
   139.8 1670.34   159.8 1659.94   179.8 1645.97   219.7 1626.76   249.7 1609.74
   259.7 1599.79   329.6 1555.09   349.6 1536.05   375.51519.014   389.5 1511.86
   409.5 1510.28   429.5 1511.11   443.51514.175   459.4 1517.62   509.4  1518.2
   529.4 1525.24   589.3 1541.09   609.3 1550.68   659.2  1556.7   679.2 1565.86
   689.2 1574.92   699.2 1580.71   759.1 1612.01     779  1627.3     819 1646.84
#Mann= 3 , 0 , 0
       0      .1       0   375.5    .045       0   443.5      .1       0
Bank Sta=375.5,443.5
XS Rating Curve= 0 ,0
Exp/Cntr=0.3,0.1

Type RM Length L Ch R = 1 ,791.1   ,452.2,448.9,445.7
XS GIS Cut Line= 3
     2006907.887      132738.157      2007642.32      132876.934
     2007708.472      132923.598
#Sta/Elev= 30
       0 1652.96    39.9 1636.92   149.5 1626.54   189.4 1619.47   199.3 1612.26
   209.3 1603.34   219.2 1597.56   249.1  1580.6   259.1 1577.02   269.1 1575.42
     289 1562.89     299 1553.18   348.8 1524.59   377.41510.582   378.7 1510.02
   445.41510.797   478.4 1517.15   548.1 1520.76   597.9 1517.82   607.9  1519.1
   617.9 1522.98   637.8 1539.77   657.7 1549.54   677.7 1553.23   707.6 1554.58
   727.5 1556.75   792.4 1573.44   801.4 1576.19   819.4 1584.92   828.4 1587.26
#Mann= 3 , 0 , 0
       0      .1       0   377.4    .045       0   445.4      .1       0
Bank Sta=377.4,445.4
XS Rating Curve= 0 ,0
Exp/Cntr=0.3,0.1

Type RM Length L Ch R = 1 ,342.2   ,342.5,342.1,341.7
XS GIS Cut Line= 3
     2006904.551      133242.007      2007313.79      133256.623
     2007723.029      133271.239
#Sta/Elev= 30
       0 1560.04      20 1556.18      40 1549.02    59.9 1546.73    89.9 1545.97
   179.8 1548.25   269.7 1552.15   299.6 1554.53   309.6 1551.64   319.6  1543.6
   339.6 1523.03   349.6  1516.2   375.51507.664   389.5  1506.8   429.5  1508.1
   443.51509.929   459.4 1513.82   489.4 1516.74   499.4 1519.27   519.4 1526.92
   539.3 1538.82   569.3 1550.98   609.3 1554.02   629.2 1564.67   689.2 1586.96
   709.1 1597.74   729.1 1605.68   769.1 1619.36     789 1627.99     819 1634.16
#Mann= 3 , 0 , 0
       0      .1       0   375.5    .045       0   443.5      .1       0
Bank Sta=375.5,443.5
XS Rating Curve= 0 ,0
Exp/Cntr=0.3,0.1

Chan Stop Cuts=-1
Use User Specified Reach Order=0
Composite Channel Slope=5